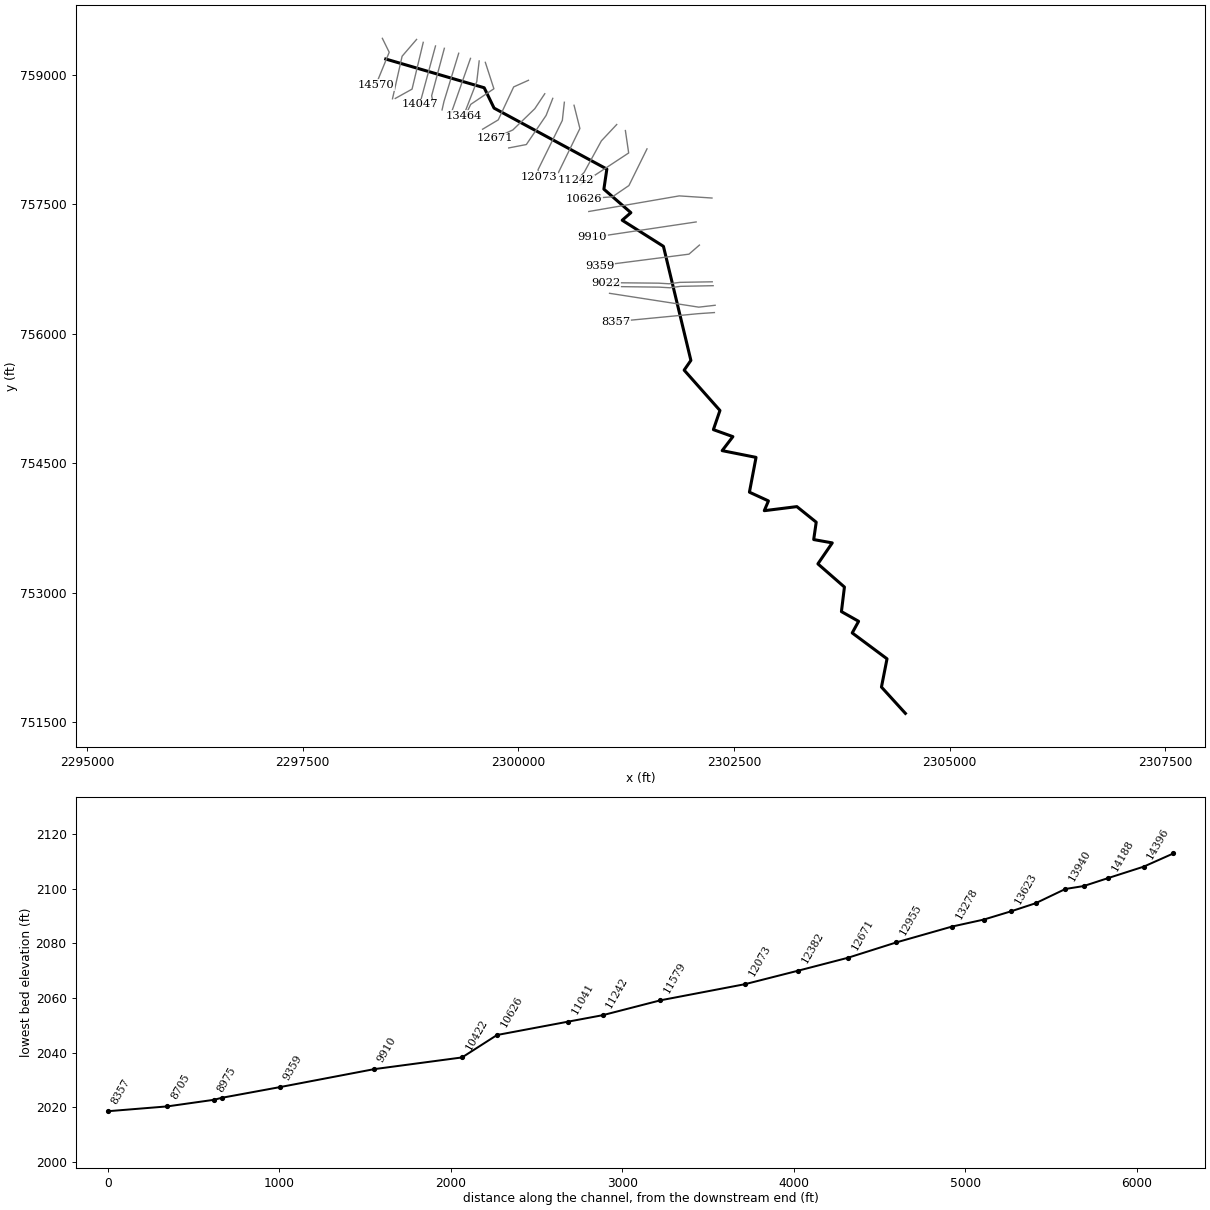
--- SALTLCKRN.prj (project) ---

Proj Title=SALTLCKRN
Current Plan=p01
Default Exp/Contr=0,0
English Units
Geom File=g01
Flow File=f01
Plan File=p01
BEGIN DESCRIPTION:
----------MODEL BY WOOD PLC 2022----------
AFH study
Randolph County, WV
HEC-RAS Version: RAS 6.2
Vertical Datum: NAVD88
Projection: NAD 1983 StatePlane West Virginia S FIPS 4702 (US Feet)
Terrain: 1-meter LIDAR (FEMA Region III 3DEP collected 2016-2018)
Land Use: 2019 NLCD
Hydrologic Method:
WV SIR2010-5033 regression equations
Additional Model Notes:
None
END DESCRIPTION:
DSS Export Rating Curves= 0
DSS Export Rating Curve Sorted= 0
DSS Export Volume Flow Curves= 0
DXF OffsetX= 0
DXF OffsetY= 0
DXF ScaleX= 0
DXF ScaleY= 0

--- SALTLCKRN.p01 (plan) ---

Plan Title=Floodplain
Program Version=6.20
Short Identifier=Floodplain
Geom File=g01
Flow File=f01
Subcritical Flow
K Sum by GR= 0
Std Step Tol= 0.01
Critical Tol= 0.01
Num of Std Step Trials= 20
Max Error Tol= 0.3
Flow Tol Ratio= 0.001
Split Flow NTrial= 30
Split Flow Tol= 0.02
Split Flow Ratio= 0.02
Log Output Level= 0
Friction Slope Method= 1
Unsteady Friction Slope Method= 2
Unsteady Bridges Friction Slope Method= 1
Parabolic Critical Depth
Global Vel Dist= 0 , 0 , 0
Global Log Level= 0
CheckData=True
Encroach Param=-1 ,0,0, 0
Mapping Interval=1HOUR
Computation Time Step Use Courant=        0
Computation Time Step Use Time Series=    0
Computation Time Step Count To Double=0
Computation Time Step Max Doubling=0
Computation Time Step Max Halving=0
Computation Time Step Residence Courant=0
Run HTab= 0
Run UNet= 0
Run Sediment= 0
Run PostProcess= 0
Run WQNet= 0
Run RASMapper=-1
UNET Theta= 0
UNET Theta Warmup= 0
UNET ZTol= 0
UNET ZSATol= 0
UNET MxIter= 0
UNET Max Iter WO Improvement= 0
UNET MaxInSteps= 0
UNET DtIC= 0
UNET DtMin= 0
UNET MaxCRTS= 0
UNET WFStab= 0
UNET SFStab= 0
UNET WFX= 1
UNET SFX= 1
UNET Gravity=32.174
UNET 1D Methodology=Finite Difference
UNET DSS MLevel= 1
UNET Pardiso=0
UNET DZMax Abort= 0
UNET Use Existing IB Tables= 0
UNET Froude Reduction=False
UNET Froude Limit= 0
UNET Froude Power= 0
UNET D1 Cores= 0
UNET WindReference=Eulerian
UNET WindDragFormulation=Hsu (1988)
UNET D2 Coriolis=0
UNET D2 Cores= 0
UNET D2 Theta= 1
UNET D2 Theta Warmup= 1
UNET D2 Z Tol= 0.01
UNET D2 Volume Tol= 0.01
UNET D2 Max Iterations= 20
UNET D2 Equation= 0
UNET D2 RampUpFraction=0.1
UNET D2 TimeSlices= 1
UNET D2 Turbulence Formulation=Non-Conservative (original)
UNET D2 Eddy Viscosity=0.3
UNET D2 Transverse Eddy Viscosity=0.1
UNET D2 Smagorinsky Mixing=0
UNET D2 BCVolumeCheck=0
UNET D2 Cores=0
UNET D2 SolverType=PARDISO (Direct)
UNET D2 Minimum Iterations= 2147483647
UNET D2 Maximum Iterations= 2147483647
UNET D2 Restart Number= 10
UNET D2 Relaxation Coeff=1.3
UNET D2 SOR Precondition Iterations= 10
UNET D2 ILUT Maximum Fill= 8
UNET D2 ILUT Tolerance=1E-08
UNET D1D2 MaxIter= 0
UNET D1D2 ZTol=0.01
UNET D1D2 QTol=0.1
UNET D1D2 MinQTol=1
Write IC File= 0
Write IC File at Fixed DateTime=0
Write IC File at Sim End=0
Echo Input=False
Echo Parameters=False
Echo Output=False
Write Detailed= 0
HDF Write Warmup=0
HDF Write Time Slices=0
HDF Flush=0
HDF Compression= 1
HDF Chunk Size= 1
HDF Spatial Parts= 1
HDF Use Max Rows=0
HDF Fixed Rows= 1
Calibration Method= 0
Calibration Iterations= 20
Calibration Max Change=0.05
Calibration Tolerance=0.2
Calibration Maximum=1.5
Calibration Minimum=0.5
Calibration Optimization Method= 1
WQ AD Non Conservative
WQ ULTIMATE=-1
WQ Max Comp Step=1HOUR
WQ Output Interval=15MIN
WQ Output Selected Increments= 0
WQ Output face flow=0
WQ Output face velocity=0
WQ Output face area=0
WQ Output face dispersion=0
WQ Output cell volume=0
WQ Output cell surface area=0
WQ Output cell continuity=0
WQ Output cumulative cell continuity=0
WQ Output face conc=0
WQ Output face dconc_dx=0
WQ Output face courant=0
WQ Output face peclet=0
WQ Output face adv mass=0
WQ Output face disp mass=0
WQ Output cell mass=0
WQ Output cell source sink temp=0
WQ Output nsm pathways=0
WQ Output nsm derived pathways=0
WQ Create Restart=0
WQ Fixed Restart=0
WQ System Summary=0
WQ Write To DSS=0
Sorting and Armoring Iterations= 10
XS Update Threshold= 0.02
Bed Roughness Predictor= 0
Hydraulics Update Threshold= 0.02
Energy Slope Method= 1
Volume Change Method= 1
Sediment Retention Method= 0
Sediment TS Multiplier= 1
Warm Up Method= 0
XS Weighting Method= 0
Number of US Weighted Cross Sections= 1
Number of DS Weighted Cross Sections= 1
Upstream XS Weight=0
Main XS Weight=1
Downstream XS Weight=0
Number of DS XS's Weighted with US Boundary= 1
Upstream Boundary Weight= 1
Weight of XSs Associated with US Boundary= 0
Number of US XS's Weighted with DS Boundary= 1
Downstream Boundary Weight= 0.5
Weight of XSs Associated with DS Boundary= 0.5
Percentile Method= 0
Sediment Output Level= 3
Mass or Volume Output= 0
Output Increment Type= 1
Profile and TS Output Increment= 1
Transport Output Increment 1
XS Output Flag= 0
XS Output Increment= 10
Read HDF5 Sediment Hotstart= 0
Sediment Hotstart Type= 0
Write Gradation File= 0
Read Gradation Hotstart= 0
Write HDF5 File= 1
Write Binary Output= 1
Write DSS Sediment File= 0
DSS Sediment Output Type= 1
SV Curve= 0
Specific Gage Flag= 0
Subcell Erosion Methods= 0
Subcell Deposition Methods= 0
Advection Scheme= 1
Matrix Solver= 0
Implicit Weighting Factor= 1
Maximum Outer Loop Convergence Iterations= 5
Convergence Maximum Absolute= 0.001
Convergence RMSE= 0.0001
Grain Fractions Max Abs Error= 0.001
Max Subgrid Regions= 1
Max Subgrid Length Scale= 3.402823E+38
Initial Layer Thickness= 3.402823E+38
Min Layer Thickness= 3.402823E+38
Max Layer Thickness= 3.402823E+38
Number of Layers= 5

--- SALTLCKRN.f01 (steady flow) ---

Flow Title=Flow
Program Version=6.20
Number of Profiles= 1
Profile Names=P100yr
River Rch & RM=SALTLCKRN,Main,14570
     379
River Rch & RM=SALTLCKRN,Main,10626
     422
River Rch & RM=SALTLCKRN,Main,7214
     469
River Rch & RM=SALTLCKRN,Main,4088
     531
Boundary for River Rch & Prof#=SALTLCKRN,Main            , 1
Up Type= 0
Dn Type= 3
Dn Slope=0.005254
DSS Import GetInterval= 0
DSS Import GetPeak= 0
DSS Import FillOption= 0

--- SALTLCKRN.g01 (geometry) ---

Geom Title=Geometry
Program Version=6.20

River Reach=SALTLCKRN       ,Main
Reach XY= 30
2298464.04448153759186.394891908     2299605.017      758853.413
     2299719.837       758617.25      2301027.23      757910.566
     2300992.855      757677.754     2301305.876      757405.358
     2301205.355      757317.337     2301683.393       757014.82
     2302001.535      755692.511      2301923.41       755579.49
     2302338.514      755111.782     2302262.429      754889.679
     2302488.558      754808.515     2302364.209      754646.189
     2302757.004      754568.064     2302680.268      754164.592
     2302900.754      754063.203      2302852.49      753950.009
     2303230.268      753997.231     2303454.573      753816.675
     2303425.407      753615.286     2303640.685      753576.571
     2303474.018      753333.515     2303781.657      753064.766
     2303746.934      752780.043      2303946.24      752667.543
     2303871.934      752532.821     2304275.505      752232.591
     2304210.986      751905.045     2304488.571       751600.06

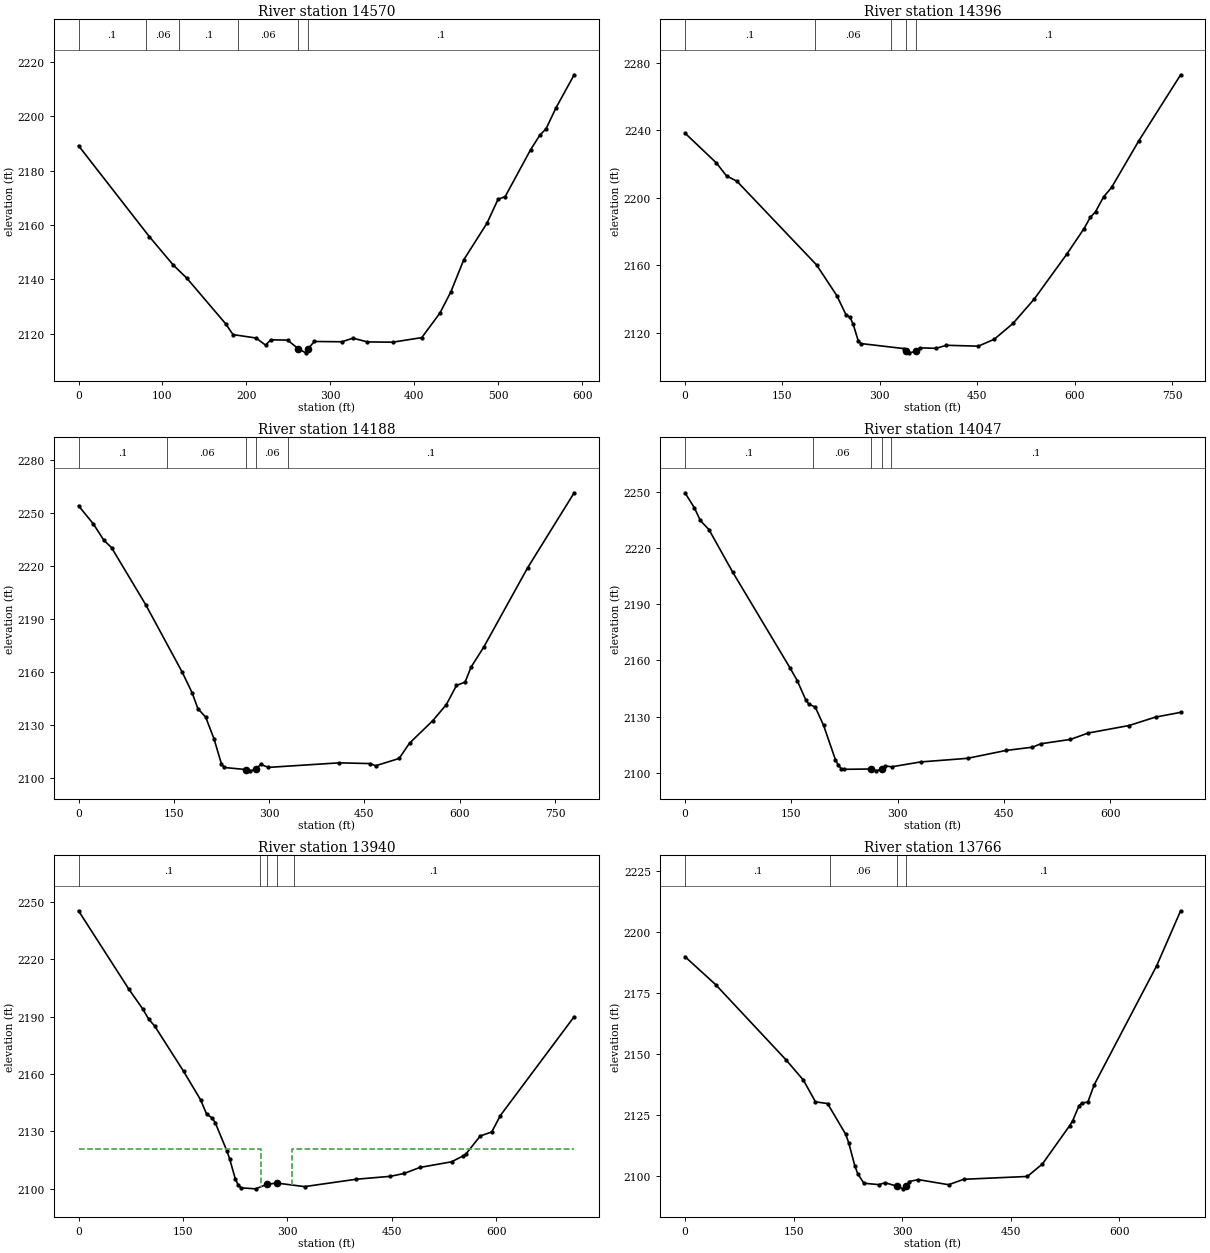
Type RM Length L Ch R = 1 ,14570   ,173.9,173.9,173.9
XS GIS Cut Line= 3
2298424.53747112759426.3746544522298504.08830898759264.862347278
2298348.60258043758885.187893846
#Sta/Elev= 30
       0 2189.14    84.3 2155.71   112.8 2145.26   129.1 2140.37   175.2 2123.65
     184 2119.66   211.5  2118.4   222.9 2115.76   228.8 2117.73   248.9 2117.64
   261.8 2114.46   270.5 2112.95  272.942114.308   280.9 2117.13   313.7 2117.02
   326.9 2118.35     344 2116.97   374.2 2116.87   408.8 2118.55   430.4 2127.57
   443.4 2135.35   458.8 2147.16   486.4  2160.6   499.6 2169.38   508.2 2170.44
   538.5 2187.71   549.2 2192.89   556.9  2195.4   568.7 2203.08   590.3 2215.21
#Mann= 6 ,-1,0
       0      .1       0      80     .06       0     120      .1       0
  190.04     .06       0   261.8    .045       0  272.94      .1       0
Bank Sta=261.8,272.94
XS Rating Curve= 0 ,0
Exp/Cntr(USF)=0,0
Exp/Cntr=0.3,0.1

Type RM Length L Ch R = 1 ,14396   ,208.8,208.8,208.8
XS GIS Cut Line= 3
2298821.23973885759413.6766156772298653.69663043759219.110425262
2298542.00122482758725.488794023
#Sta/Elev= 30
       0 2238.43    48.2  2220.8      64 2213.03    79.8 2209.94   202.5 2160.26
   233.7 2142.03   247.9 2130.63     254 2129.14   258.7 2125.28   266.9 2114.95
     271 2113.59   336.6 2110.63   340.8 2108.93   344.9 2108.09   355.82108.991
   361.3 2111.04   386.7 2110.77   402.3 2112.57   451.5 2112.05   476.1 2116.17
   504.8  2125.5   537.6 2140.01   587.4 2166.49   614.2 2181.76   623.7 2188.39
   631.9 2191.78   644.2 2200.53   656.6 2206.19   698.6 2233.91   762.9 2273.03
#Mann= 5 ,-1,0
       0      .1       0     200     .06       0  316.76      .1       0
   340.8    .045       0   355.8      .1       0
Bank Sta=340.8,355.8
XS Rating Curve= 0 ,0
Exp/Cntr(USF)=0,0
Exp/Cntr=0.3,0.1

Type RM Length L Ch R = 1 ,14188   ,140.3,140.3,140.3
XS GIS Cut Line= 3
 2298898.5398274759379.8911637372298768.82903379758837.627984895
2298574.26284337758729.535656887
#Sta/Elev= 30
       0 2254.17    23.4 2243.81    39.8 2234.65    52.1 2230.33   105.6 2198.16
   163.2 2159.83   178.9 2148.06   187.9 2139.11   200.2 2134.29   213.3 2121.97
   224.9 2107.85     229 2105.79   263.1 2104.63   270.1 2103.88   279.12104.723
   286.6 2107.56   298.9 2105.83     410 2108.41   459.3    2108   467.5 2106.75
   504.6 2110.89     521 2119.57   557.6 2132.33     579 2141.47   594.9 2152.32
   608.4 2154.16   617.8 2162.66   637.8 2174.02   706.7 2218.88   780.1 2261.49
#Mann= 5 ,-1,0
       0      .1       0     140     .06       0   263.1    .045       0
   279.1     .06       0     330      .1       0
Bank Sta=263.1,279.1
XS Rating Curve= 0 ,0
Exp/Cntr(USF)=0,0
Exp/Cntr=0.3,0.1

Type RM Length L Ch R = 1 ,14047   ,107.2,107.2,107.2
XS GIS Cut Line= 2
2299040.74781025759338.0124529252298857.88219818758663.037287963
#Sta/Elev= 30
       0 2249.62    13.3 2241.56    21.6 2234.85      34 2229.83    67.2 2207.29
   148.2 2156.02   158.3 2149.26   170.8 2138.61   174.9 2136.61   183.8 2135.09
   195.6 2125.25   212.2    2107   216.3 2104.07   220.5 2102.16   224.7 2101.82
   262.2 2101.98   270.2    2101   277.42101.971   282.7 2103.68   291.4 2103.14
   332.4 2105.75   398.7 2107.69   452.6 2111.88   490.3 2113.65   502.3 2115.49
   543.8 2117.79   568.8 2121.19   626.6 2125.23   663.9 2129.74   699.3 2132.25
#Mann= 5 ,-1,0
       0      .1       0     180     .06       0   262.2    .045       0
   277.4     .06       0     290      .1       0
Bank Sta=262.2,277.4
XS Rating Curve= 0 ,0
Exp/Cntr(USF)=0,0
Exp/Cntr=0.3,0.1

Type RM Length L Ch R = 1 ,13940   ,173.6,173.6,173.6
BEGIN DESCRIPTION:
Structure
END DESCRIPTION:
XS GIS Cut Line= 3
2299143.25951854759310.8486176622298996.00351993758760.901407228
2299025.94227999758621.389929075
#Sta/Elev= 30
       0 2245.32    72.1 2204.45    92.1 2194.07   101.1 2188.49   109.4 2185.08
   150.9 2161.39   175.6 2146.31   183.9 2139.08   192.2 2136.88   196.4  2134.5
   212.9 2119.96   217.1  2115.6   225.3 2105.03   229.5 2101.87   233.6 2100.44
   254.3 2099.92   270.9 2102.29   284.8 2102.94   324.7 2101.08   399.1 2104.95
   448.1 2106.47   467.7 2107.96   490.4 2111.11   535.9 2114.06   552.5 2117.13
   556.6 2118.19   577.2 2127.59   593.6 2129.66   605.9 2138.21     712 2189.94
#Mann= 5 ,-1,0
       0      .1       0     260     .06       0   270.9    .045       0
   284.8     .06       0     310      .1       0
#XS Ineff= 2 , 0
          262.82 2120.66  306.14         2120.97
Permanent Ineff=
       F       F
Bank Sta=270.9,284.8
XS Rating Curve= 0 ,0
Exp/Cntr(USF)=0,0
Exp/Cntr=0.3,0.1

Type RM Length L Ch R = 1 ,13766   ,143.3,143.3,143.3
XS GIS Cut Line= 3
2299309.72653702759253.5942922662299138.58035101758693.315725422
2299116.77544235758596.661199714
#Sta/Elev= 30
       0 2189.95    42.3  2178.5   139.3 2147.72   163.6 2139.32   180.3 2130.39
     197 2129.69   222.1 2117.08   226.3 2113.54   234.7 2104.11   238.8 2100.87
   247.2    2097   268.1 2096.42   276.5 2097.21   292.8  2095.8   301.6  2094.7
   305.9  2095.9   309.9 2097.71   322.5 2098.48   364.3 2096.39   385.2 2098.62
   473.1 2099.78     494 2104.94   531.6 2120.64   535.8 2122.66   544.2  2128.6
   548.3 2129.88   556.7  2130.3   565.4 2137.34   651.6  2186.1   684.9 2208.77
#Mann= 4 ,-1,0
       0      .1       0     200     .06       0   292.8    .045       0
   305.9      .1       0
Bank Sta=292.8,305.9
XS Rating Curve= 0 ,0
Exp/Cntr(USF)=0,0
Exp/Cntr=0.3,0.1

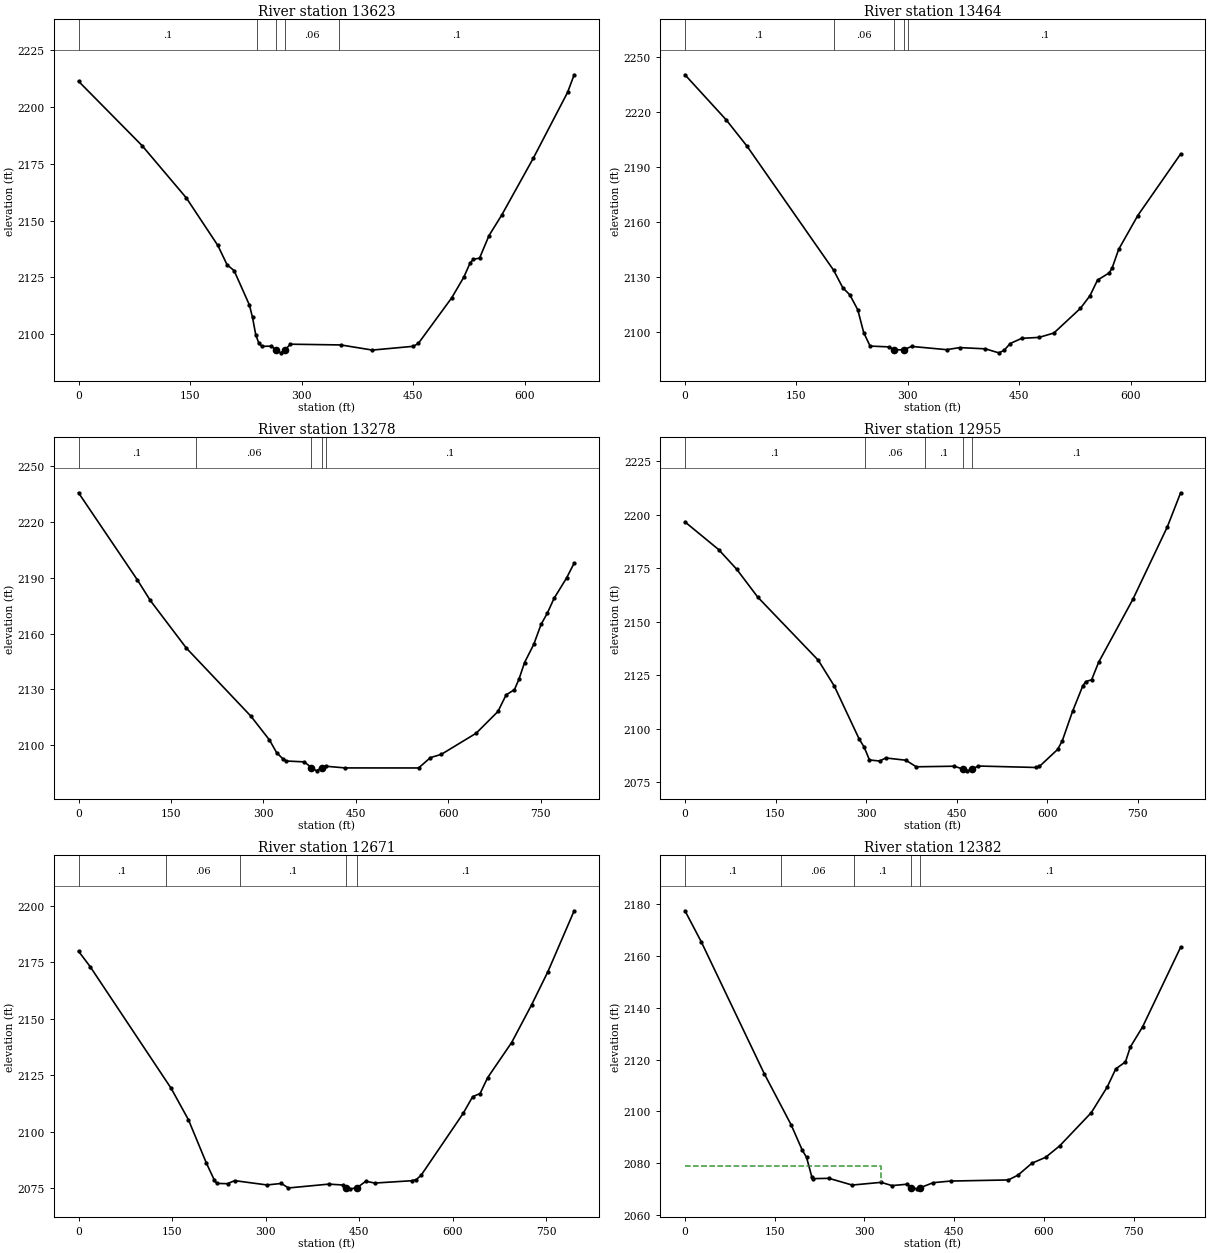
Type RM Length L Ch R = 1 ,13623   ,158.8,158.8,158.8
XS GIS Cut Line= 2
2299446.37370249 759193.888882062299224.78443008758565.151840811
#Sta/Elev= 30
       0 2211.43    85.6 2183.02     145 2160.02   187.4 2139.05   199.8 2130.55
   209.3 2127.95   229.8 2112.85     234 2107.38   238.3 2099.78   242.5    2096
   246.7  2094.6   259.5 2094.69   265.42093.075     272 2091.74   278.2 2093.21
   284.9 2095.55   352.8 2095.22   395.2 2092.96   450.3 2094.62     457 2095.87
   501.9 2115.98   518.2  2125.1   526.7 2131.38   530.9  2132.9   539.4 2133.52
   552.1 2143.43   569.1 2152.42   611.5 2177.43   657.7  2206.5   666.6 2214.28
#Mann= 5 ,-1,0
       0      .1       0     240     .06       0   265.4    .045       0
   278.2     .06       0     350      .1       0
Bank Sta=265.4,278.2
XS Rating Curve= 0 ,0
Exp/Cntr(USF)=0,0
Exp/Cntr=0.3,0.1

Type RM Length L Ch R = 1 ,13464   ,185.9,185.9,185.9
XS GIS Cut Line= 3
2299547.02796223759164.1962982522299519.45450869758925.513590982
2299365.21550291758527.421855392
#Sta/Elev= 30
       0 2240.41    55.4 2215.87    83.6 2201.42   200.2 2133.73   212.4 2124.25
   221.9 2120.35   232.6 2112.21   240.6 2099.72   249.2 2092.41   274.9 2091.96
   281.5 2090.36   294.32090.381     305 2092.22   352.2 2090.45   369.8 2091.58
   404.4  2090.9   422.4 2088.72   429.4 2090.03   437.8 2093.81   453.3 2096.64
   476.6 2097.14   496.6 2099.54   532.3 2112.99   545.2 2119.91   555.3 2128.39
   571.3 2132.41   575.2 2135.25   583.8 2145.18   609.5 2163.61   667.2 2197.21
#Mann= 5 ,-1,0
       0      .1       0     200     .06       0   281.5    .045       0
   294.3     .06       0  300.27      .1       0
Bank Sta=281.5,294.3
XS Rating Curve= 0 ,0
Exp/Cntr(USF)=0,0
Exp/Cntr=0.3,0.1

Type RM Length L Ch R = 1 ,13278   ,323.4,323.4,323.4
XS GIS Cut Line= 4
 2299618.3648722759147.9759043392299717.65199916758841.840596183
2299449.34035843758660.9961863462299379.60297163758517.975443926
#Sta/Elev= 30
       0 2235.81    95.5 2188.93   116.5 2177.85   175.1  2152.2   279.9 2115.54
   309.9 2102.77   321.8 2095.81     332 2092.55   337.3 2091.44   366.6 2090.97
   378.1 2087.84   386.3 2086.15   394.6 2087.82   401.2 2088.63   432.9 2087.72
     552  2087.7   571.2 2093.27   588.9 2095.03   645.4 2106.39   680.8  2118.1
   694.1 2127.06   707.5 2129.82   714.9 2135.47   723.9 2144.37   738.9 2154.21
   750.8 2164.98   760.9    2171   771.8 2178.94   792.1 2189.91   804.5 2197.95
#Mann= 5 ,-1,0
       0      .1       0     190     .06       0   378.1    .045       0
   394.6     .06       0  401.83      .1       0
Bank Sta=378.1,394.6
XS Rating Curve= 0 ,0
Exp/Cntr(USF)=0,0
Exp/Cntr=0.3,0.1

Type RM Length L Ch R = 1 ,12955   ,283.6,283.6,283.6
XS GIS Cut Line= 4
2300118.34647586758939.9457335462299946.95798288758863.116409105
2299768.47755226758481.3337661162299586.45115281758372.590722293
#Sta/Elev= 30
       0 2196.69    55.7 2183.79    85.7 2174.58   120.7 2161.51   220.9 2132.05
   247.4    2120   288.8 2095.14   296.7 2091.56   305.7 2085.46   322.4 2084.95
   332.8 2086.39   365.9 2085.33   383.3 2082.26   446.1 2082.53   460.52081.205
   468.1 2080.37   476.22081.234   485.8 2082.62   581.6 2081.94   587.4 2082.45
   617.4 2090.35   625.2  2094.4   642.2 2108.16   659.2  2120.1   664.2  2122.1
   673.8 2122.92   685.4 2131.08   742.2 2160.54   799.2 2194.34   821.3 2210.31
#Mann= 5 ,-1,0
       0      .1       0  297.82     .06       0  397.82      .1       0
   460.5    .045       0   476.2      .1       0
Bank Sta=460.5,476.2
XS Rating Curve= 0 ,0
Exp/Cntr(USF)=0,0
Exp/Cntr=0.3,0.1

Type RM Length L Ch R = 1 ,12671   ,289.1,289.1,289.1
XS GIS Cut Line= 4
2300307.46481295758783.9231054512300191.62983148758610.170633255
2299937.50206603758364.3167950452299725.92592641 758267.39364729
#Sta/Elev= 30
       0 2179.88    18.8    2173   148.6 2119.19   176.4 2105.25   205.2 2086.06
   217.6 2078.75   221.8 2077.12     239    2077   250.5 2078.35   302.3 2076.44
   325.3  2077.1   336.8 2075.11   401.5 2076.81   424.1 2076.42   429.8  2075.3
   436.3 2074.72   446.8 2075.23   460.9 2078.07   475.2 2077.28   534.5 2078.31
     542 2078.84   549.7 2080.77   617.1 2108.13   632.2 2115.49   644.2  2116.9
   656.3 2123.91   694.8 2139.47   726.7 2156.08   752.9 2170.78   795.1 2197.76
#Mann= 5 ,-1,0
       0      .1       0     140     .06       0  258.82      .1       0
   429.8    .045       0   446.8      .1       0
Bank Sta=429.8,446.8
XS Rating Curve= 0 ,0
Exp/Cntr(USF)=0,0
Exp/Cntr=0.3,0.1

Type RM Length L Ch R = 1 ,12382   ,309.3,309.3,309.3
XS GIS Cut Line= 4
 2300400.3020707758730.6314258962300322.96201001758532.173911672
 2300093.8603208758195.0879867762299889.56582086758155.688333217
#Sta/Elev= 30
       0 2177.53    27.3  2165.5   132.5 2114.56   177.6 2094.71   195.8  2085.1
   203.3 2082.13   211.9 2074.74   214.3 2073.96   240.8 2074.07   279.5 2071.47
   327.9 2072.52     346 2071.26   371.4  2071.8   378.4 2070.48   388.7 2070.01
   392.8  2070.4   414.9 2072.39   443.9 2073.02   540.7 2073.45   556.9 2075.34
     580 2079.92     603 2082.21   626.4 2086.63   679.3 2099.49   706.1 2109.48
   720.1 2116.38   736.4 2119.12   744.5 2124.85   764.9  2132.6   828.6 2163.45
#Mann= 5 ,-1,0
       0      .1       0     160     .06       0  282.99      .1       0
   378.4    .045       0   392.8      .1       0
#XS Ineff= 2 , 0
          327.73 2079.01
Permanent Ineff=
       F       F
Bank Sta=378.4,392.8
XS Rating Curve= 0 ,0
Exp/Cntr(USF)=0,0
Exp/Cntr=0.3,0.1

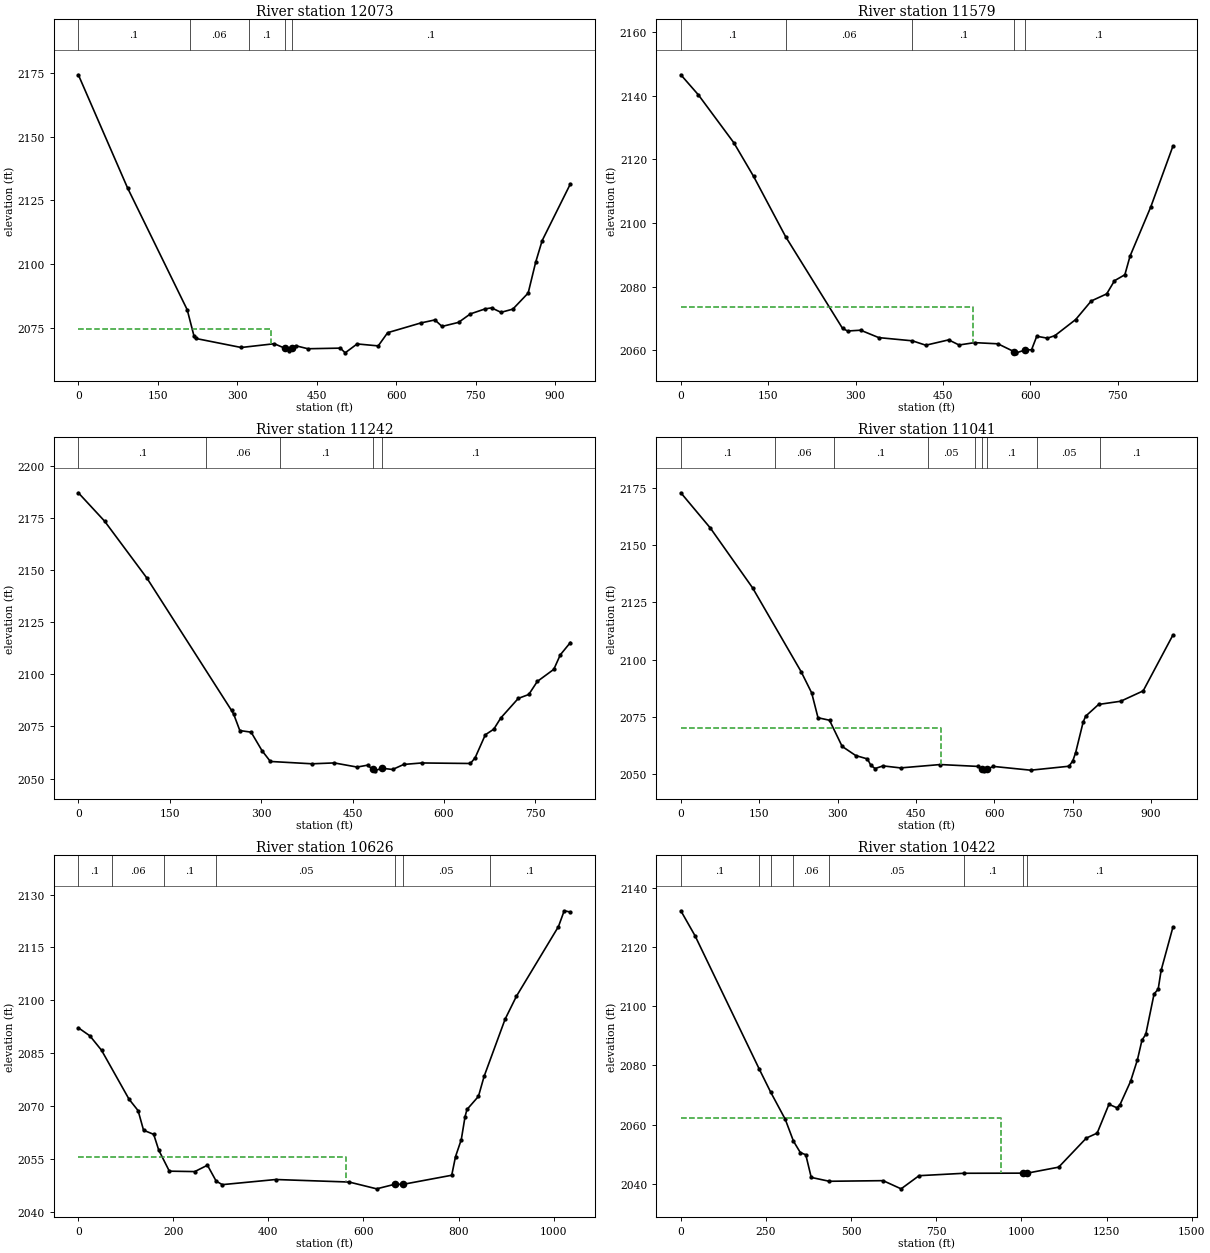
Type RM Length L Ch R = 1 ,12073   ,493.6,493.6,493.6
XS GIS Cut Line= 4
2300534.55274209758685.3947866242300511.20479924758475.263300975
2300229.57023861757903.2387011522300241.24421004757824.439394034
#Sta/Elev= 30
       0 2174.36    92.8 2129.94   205.5 2082.01   218.2 2071.77   221.2 2070.75
   307.4 2067.18   369.8 2068.66   390.3 2066.84   397.5 2065.73   403.5 2066.83
   409.9 2067.89   433.3 2066.69   494.6 2066.93   503.6 2065.08   526.2 2068.58
     566 2067.81   583.8    2073   646.2 2076.81     673 2078.02   686.4 2075.46
   717.6 2077.05   739.9 2080.38   767.9 2082.36   779.9 2082.75   797.8    2081
   820.1 2082.26     849 2088.58   863.2 2100.71   875.4 2109.18   928.7 2131.48
#Mann= 5 ,-1,0
       0      .1       0     210     .06       0  321.42      .1       0
   390.3    .045       0   403.5      .1       0
#XS Ineff= 2 , 0
          364.55 2074.64
Permanent Ineff=
       F       F
Bank Sta=390.3,403.5
XS Rating Curve= 0 ,0
Exp/Cntr(USF)=0,0
Exp/Cntr=0.3,0.1

Type RM Length L Ch R = 1 ,11579   ,337.1,337.1,337.1
XS GIS Cut Line= 3
2300646.91471706 758650.372872352300714.79574287758381.063705645
2300466.29387122757870.991786685
#Sta/Elev= 30
       0 2146.64    30.1 2140.33      91 2125.26     125 2114.66   179.9 2095.73
   277.7 2066.86   286.5 2066.03   308.8 2066.28   339.9 2063.95   397.7 2062.94
   420.7 2061.56     460 2063.24   477.8 2061.63   504.5 2062.37   544.6    2062
   572.62059.507   575.7 2059.16   590.32059.975   602.4 2060.16   611.3 2064.38
   629.7 2063.77   642.5 2064.58   678.1 2069.63   704.8 2075.47   731.4 2077.71
   744.8 2081.85   762.6 2083.73   771.5 2089.59   807.1 2105.06   845.1 2124.16
#Mann= 5 ,-1,0
       0      .1       0     180     .06       0  397.73      .1       0
   572.6    .045       0   590.3      .1       0
#XS Ineff= 2 , 0
          502.38 2073.48
Permanent Ineff=
       F       F
Bank Sta=572.6,590.3
XS Rating Curve= 0 ,0
Exp/Cntr(USF)=0,0
Exp/Cntr=0.3,0.1

Type RM Length L Ch R = 1 ,11242   ,201,201,201
XS GIS Cut Line= 4
2301141.59925619758427.1081688472300963.57119196758237.406133192
2300764.45789229757872.8936260592300672.63399789757778.238529399
#Sta/Elev= 30
       0 2187.15      43 2173.57   112.4 2146.26   251.4 2082.69     255 2080.84
     265 2073.04   283.5 2072.27   301.4 2063.39   315.1 2058.21   383.5 2057.09
   419.9 2057.51   457.4 2055.52   474.6 2056.43   482.82054.406   486.9 2053.71
   497.52054.967   515.7 2054.36   533.9 2056.78   563.5 2057.49   643.3 2057.24
   651.1 2059.98   667.8 2071.01   681.7  2073.7   693.1 2079.05   721.9 2088.47
   739.1 2090.35   753.1  2096.6   780.2 2102.42   790.8 2109.36   807.4 2115.29
#Mann= 5 ,-1,0
       0      .1       0     210     .06       0  330.16      .1       0
   482.8    .045       0   497.5      .1       0
Bank Sta=482.8,497.5
XS Rating Curve= 0 ,0
Exp/Cntr(USF)=0,0
Exp/Cntr=0.3,0.1

Type RM Length L Ch R = 1 ,11041   ,415.2,415.2,415.2
XS GIS Cut Line= 3
2301242.28725973758357.0643402972301280.22766686758097.318476092
2300712.58080632757723.751390493
#Sta/Elev= 30
       0 2172.86    56.5 2157.45   137.3 2131.33   230.3 2094.67   250.5  2085.4
   262.6 2074.55   284.6 2073.46   308.8 2062.03   334.8 2058.03   357.3 2056.55
   363.7 2053.75   371.9 2052.36   387.1 2053.51   420.6 2052.63   496.6  2054.1
     569 2053.28   575.92052.004   580.3 2051.35   585.2 2051.96   598.3 2053.28
   669.8 2051.63     743 2053.36   750.3 2055.67   755.8 2059.27   770.1 2072.57
   774.9 2075.22   799.8 2080.37     842 2081.76   885.1 2086.29     942 2110.67
#Mann= 9 ,-1,0
       0      .1       0     180     .06       0   292.5      .1       0
   472.5     .05       0   562.5      .1       0   575.9    .045       0
   585.2      .1       0   682.5     .05       0   802.5      .1       0
#XS Ineff= 2 , 0
          498.85 2069.89
Permanent Ineff=
       F       F
Bank Sta=575.9,585.2
XS Rating Curve= 0 ,0
Exp/Cntr(USF)=0,0
Exp/Cntr=0.3,0.1

Type RM Length L Ch R = 1 ,10626   ,203.8,203.8,203.8
BEGIN DESCRIPTION:
Structure-- Aggressive IFA needed as channel was not wetted without it
END DESCRIPTION:
XS GIS Cut Line= 4
2301492.83640808758144.9081630252301283.22363989757719.614468036
2301092.27522687757589.2109688252300763.14050792 757564.38997118
#Sta/Elev= 30
       0  2092.2    24.2 2089.92    48.8 2085.82   106.7 2071.91   125.8 2068.66
   137.2 2063.11   158.6 2061.92   169.2 2057.45   191.5 2051.47     245 2051.35
   271.7 2053.16     290 2048.65   302.9 2047.64   415.5  2049.1   569.9 2048.38
   627.8 2046.45   666.7 2047.78   682.22047.701   785.7 2050.31   793.7 2055.61
   805.8 2060.42   813.8 2066.99   817.8 2068.99   841.9 2072.71   853.9 2078.42
     898 2094.63   921.8 2101.14  1010.3 2120.95  1022.4 2125.43  1035.4 2125.07
#Mann= 7 ,-1,0
       0      .1       0      70     .06       0     180      .1       0
     290     .05       0   666.7    .045       0   682.2     .05       0
  865.37      .1       0
#XS Ineff= 2 , 0
          562.79 2055.37
Permanent Ineff=
       F       F
Bank Sta=666.7,682.2
XS Rating Curve= 0 ,0
Exp/Cntr(USF)=0,0
Exp/Cntr=0.3,0.1

Type RM Length L Ch R = 1 ,10422   ,512.7,512.7,512.7
XS GIS Cut Line= 3
2302246.24880228757574.9082548252301866.84473096757599.715444103
2300817.64654915757418.768887016
#Sta/Elev= 30
       0 2132.35    41.7 2123.89   230.6 2078.69   263.7 2070.99   306.7 2061.75
   330.8 2054.36   350.8 2050.53   366.9 2049.77   382.9 2042.11   435.7  2040.8
     594 2041.01   646.8 2038.24   699.5 2042.69   831.6 2043.51  1003.3 2043.55
  1016.92043.545  1109.5 2045.58  1190.7 2055.42  1222.5  2057.1  1257.1 2066.85
    1280  2065.7  1289.5 2066.71  1320.6 2074.61  1340.9 2081.98  1354.1 2088.57
  1365.2 2090.51  1389.6 2104.19  1401.7 2105.82  1410.4 2112.21  1444.9 2126.77
#Mann= 8 ,-1,0
       0      .1       0   230.6     .06       0   263.7      .1       0
   330.8     .06       0   435.7     .05       0   831.6      .1       0
  1003.3    .045       0  1016.9      .1       0
#XS Ineff= 2 , 0
          940.15  2062.1
Permanent Ineff=
       F       F
Bank Sta=1003.3,1016.9
XS Rating Curve= 0 ,0
Exp/Cntr(USF)=0,0
Exp/Cntr=0.3,0.1

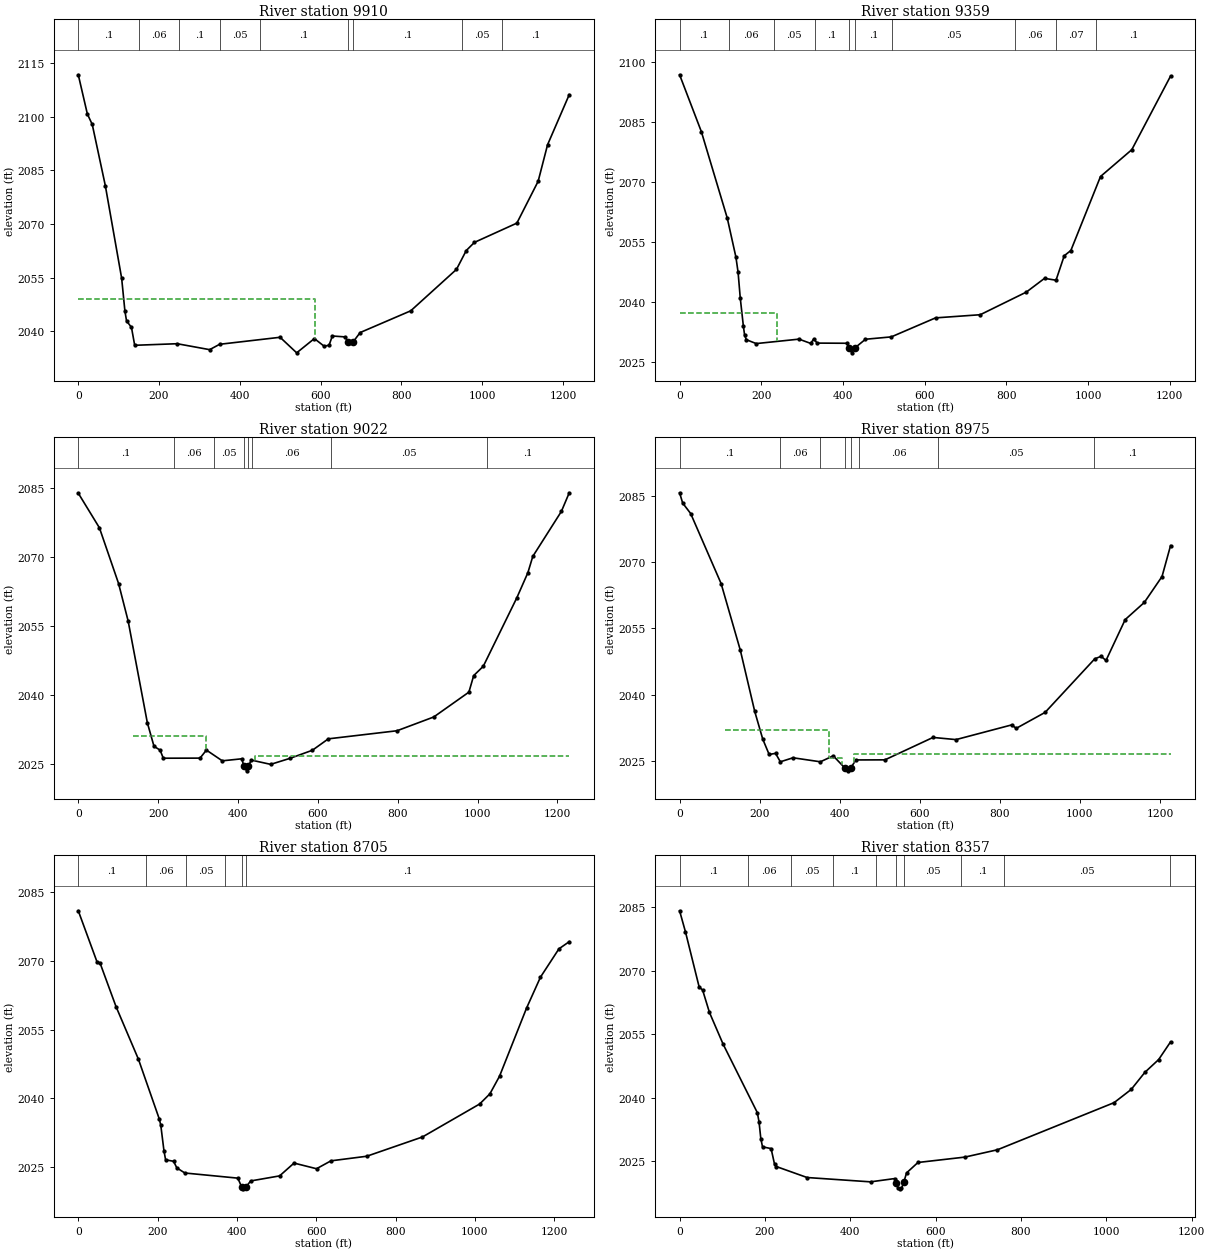
Type RM Length L Ch R = 1 ,9910    ,550.5,550.5,550.5
XS GIS Cut Line= 2
2302062.38375233757297.6514334822300859.96469556757118.164122823
#Sta/Elev= 30
       0  2111.7    22.5 2100.73    34.6 2097.81    66.9 2080.74   107.4 2054.81
   115.5  2045.6   119.5 2042.88   131.7 2041.07   139.7 2036.06   244.9  2036.5
   325.3 2034.84     350 2036.34   499.7  2038.3   540.8 2033.95   584.6 2037.94
   608.9 2035.79     621 2036.09   629.1 2038.66   661.5  2038.4   667.5 2036.99
   680.5    2037   697.9 2039.62   823.2  2045.7   936.5 2057.29   960.7 2062.56
     981 2064.84    1086 2070.22  1138.7 2081.92    1162 2092.13  1215.7 2106.15
#Mann= 9 ,-1,0
       0      .1       0     150     .06       0     250      .1       0
     350     .05       0     450      .1       0   667.5    .045       0
   680.5      .1       0     950     .05       0    1050      .1       0
#XS Ineff= 2 , 0
          585.64 2049.02
Permanent Ineff=
       F       F
Bank Sta=667.5,680.5
XS Rating Curve= 0 ,0
Exp/Cntr(USF)=0,0
Exp/Cntr=0.3,0.1

Type RM Length L Ch R = 1 ,9359    ,336.9,336.9,336.9
BEGIN DESCRIPTION:
Structure XS 34
END DESCRIPTION:
XS GIS Cut Line= 3
2302100.32415946757029.1500907082301979.20670593756924.084347883
2300946.06023482756791.292922924
#Sta/Elev= 30
       0 2096.73    53.2 2082.57   116.7 2060.99   137.9 2051.24   143.2 2047.46
   148.5 2041.07     156 2034.16   159.1 2031.83   163.4 2030.64   187.6 2029.67
   292.4 2030.78   320.7 2029.72   328.7 2030.83   336.8 2029.79   409.4 2029.75
   414.6 2028.51   421.5 2027.36   429.6 2028.63   455.1 2030.75   518.3 2031.34
   626.6 2036.08   736.1 2036.87     849 2042.52   893.4 2045.94   921.6 2045.48
   941.7 2051.58   957.9 2052.89  1030.5 2071.35  1107.1 2078.04    1202  2096.4
#Mann= 10 ,-1,0
       0      .1       0     120     .06       0  230.34     .05       0
  330.34      .1       0   414.6    .045       0   429.6      .1       0
  520.34     .05       0  820.34     .06       0  920.34     .07       0
 1020.34      .1       0
#XS Ineff= 2 , 0
          238.21 2037.19
Permanent Ineff=
       F       F
Bank Sta=414.6,429.6
XS Rating Curve= 0 ,0
Exp/Cntr(USF)=0,0
Exp/Cntr=0.5,0.3

Type RM Length L Ch R = 1 ,9022    ,47.3,47.3,47.3
BEGIN DESCRIPTION:
Structure XS 3 16.5ft
END DESCRIPTION:
XS GIS Cut Line= 5
2302249.02177239756603.7095433482301872.91267952 756597.20860051
2301748.80377081756580.6607460152301626.71793012756587.924590491
2301020.88604351756593.803848311
#Sta/Elev= 30
       0 2083.94    52.9 2076.41   100.9 2064.27   124.9  2056.1   172.9 2033.97
   189.6 2028.82   204.9 2027.98   212.9 2026.22   304.9 2026.24   320.9 2027.99
   360.6 2025.65   409.2 2026.09   414.82024.573   421.3 2023.47   426.22024.584
   433.4 2025.81   481.8 2024.88   530.1 2026.19   586.2 2027.95   626.2 2030.44
   798.2  2032.2   890.2  2035.2   978.2 2040.61   990.2 2044.21  1014.2 2046.24
  1098.2 2061.15  1125.9 2066.62  1138.2 2070.17  1209.8 2079.97  1229.5 2084.03
#Mann= 8 ,-1,0
       0      .1       0     240     .06       0     340     .05       0
   414.8    .045       0   426.2     .05       0  436.17     .06       0
  633.67     .05       0 1023.67      .1       0
#XS Ineff= 4 ,-1
       0  137.03  2025.6  137.03  321.05 2031.11  321.05  398.27  2025.6
  442.68  1229.5  2026.6
Permanent Ineff=
       F       F       F       F
Bank Sta=414.8,426.2
XS Rating Curve= 0 ,0
Exp/Cntr(USF)=0,0
Exp/Cntr=0.5,0.3

Type RM Length L Ch R = 1 ,8975    ,270.1,270.1,270.1
BEGIN DESCRIPTION:
Structure XS 2 20.3ft 6.77
END DESCRIPTION:
XS GIS Cut Line= 5
2302259.83479163756558.5677912982301881.59811747756551.003057814
2301757.48920876756534.4552033192301635.40336807756541.719047795
2301034.89043469756549.725886907
#Sta/Elev= 30
       0 2085.74     7.7 2083.41    27.7 2081.03   103.7 2065.17   151.7 2050.06
   187.7 2036.18   207.7 2029.92   223.7 2026.43   239.7 2026.68   251.7 2024.77
   283.4 2025.68   351.7 2024.77   383.8 2026.12     412 2023.44   420.1 2022.72
   428.2 2023.45   440.3 2025.19   512.9 2025.21   633.1 2030.29   690.5  2029.8
   829.1 2033.12   841.1 2032.36   913.1 2035.97  1037.1 2048.11  1053.1 2048.68
  1065.1 2047.73  1113.1    2057  1160.8 2060.88  1205.1 2066.76  1226.4 2073.77
#Mann= 8 ,-1,0
       0      .1       0     250     .06       0     350     .05       0
     412    .045       0   428.2     .05       0  448.31     .06       0
  645.82     .05       0 1035.82      .1       0
#XS Ineff= 4 ,-1
       0  113.96  2025.6  113.96  372.75 2031.87  372.75  405.23  2025.6
  434.97  1226.4  2026.6
Permanent Ineff=
       F       F       F       F
Bank Sta=412,428.2
XS Rating Curve= 0 ,0
Exp/Cntr(USF)=0,0
Exp/Cntr=0.5,0.3

Type RM Length L Ch R = 1 ,8705    ,348.2,348.2,348.2
BEGIN DESCRIPTION:
Structure XS 1
END DESCRIPTION:
XS GIS Cut Line= 3
2302282.72996298756331.6302980662302093.02792732756309.741601645
2301058.42220979756470.258708738
#Sta/Elev= 30
       0 2080.89    46.9 2069.84    54.9  2069.5    95.2 2060.01   151.6 2048.57
     204  2035.6     208  2034.2   216.1 2028.57   220.2 2026.64   240.3 2026.32
   248.5 2024.88   268.7 2023.77   402.3 2022.65     412 2020.71   415.5 2020.32
   422.6 2020.72   434.7 2022.04   507.6 2023.14     544 2025.93   600.7  2024.7
   637.1 2026.42   727.4 2027.42   867.8 2031.62    1012  2038.8  1037.8 2041.01
  1062.1 2044.85  1130.3  2059.7  1165.4 2066.44  1211.9  2072.6  1237.9 2074.16
#Mann= 6 ,-1,0
       0      .1       0     170     .06       0  270.96     .05       0
  370.96      .1       0     412    .045       0   422.6      .1       0
Bank Sta=412,422.6
XS Rating Curve= 0 ,0
Exp/Cntr(USF)=0,0
Exp/Cntr=0.3,0.1

Type RM Length L Ch R = 1 ,8357    ,398.2,398.2,398.2
XS GIS Cut Line= 3
2302273.97448441756246.9940052352302084.27244875756233.860787382
2301128.46603834756141.928262411
#Sta/Elev= 30
       0 2084.16    13.8 2079.17    45.9 2066.15    53.9 2065.47      70 2060.16
     102 2052.68   182.2 2036.51   186.2 2034.31   190.3 2030.41   194.3 2028.45
   214.4 2028.04   222.4  2024.4   226.4 2023.81   298.8 2021.21   447.4 2020.19
   503.7 2020.96   507.12020.018   511.7 2018.69   515.7 2018.54   519.8 2018.63
   525.22020.062   531.8  2022.3   558.5 2024.76   668.5 2026.03   744.8 2027.76
  1018.1 2038.88  1058.2    2042  1090.4 2046.05  1122.5 2049.05  1150.4 2053.22
#Mann= 10 ,-1,0
       0      .1       0     160     .06       0  260.16     .05       0
  360.16      .1       0  460.16     .05       0   507.1    .045       0
   525.2     .05       0  660.16      .1       0  760.16     .05       0
 1150.16      .1       0
Bank Sta=507.1,525.2
XS Rating Curve= 0 ,0
Exp/Cntr(USF)=0,0
Exp/Cntr=0.3,0.1