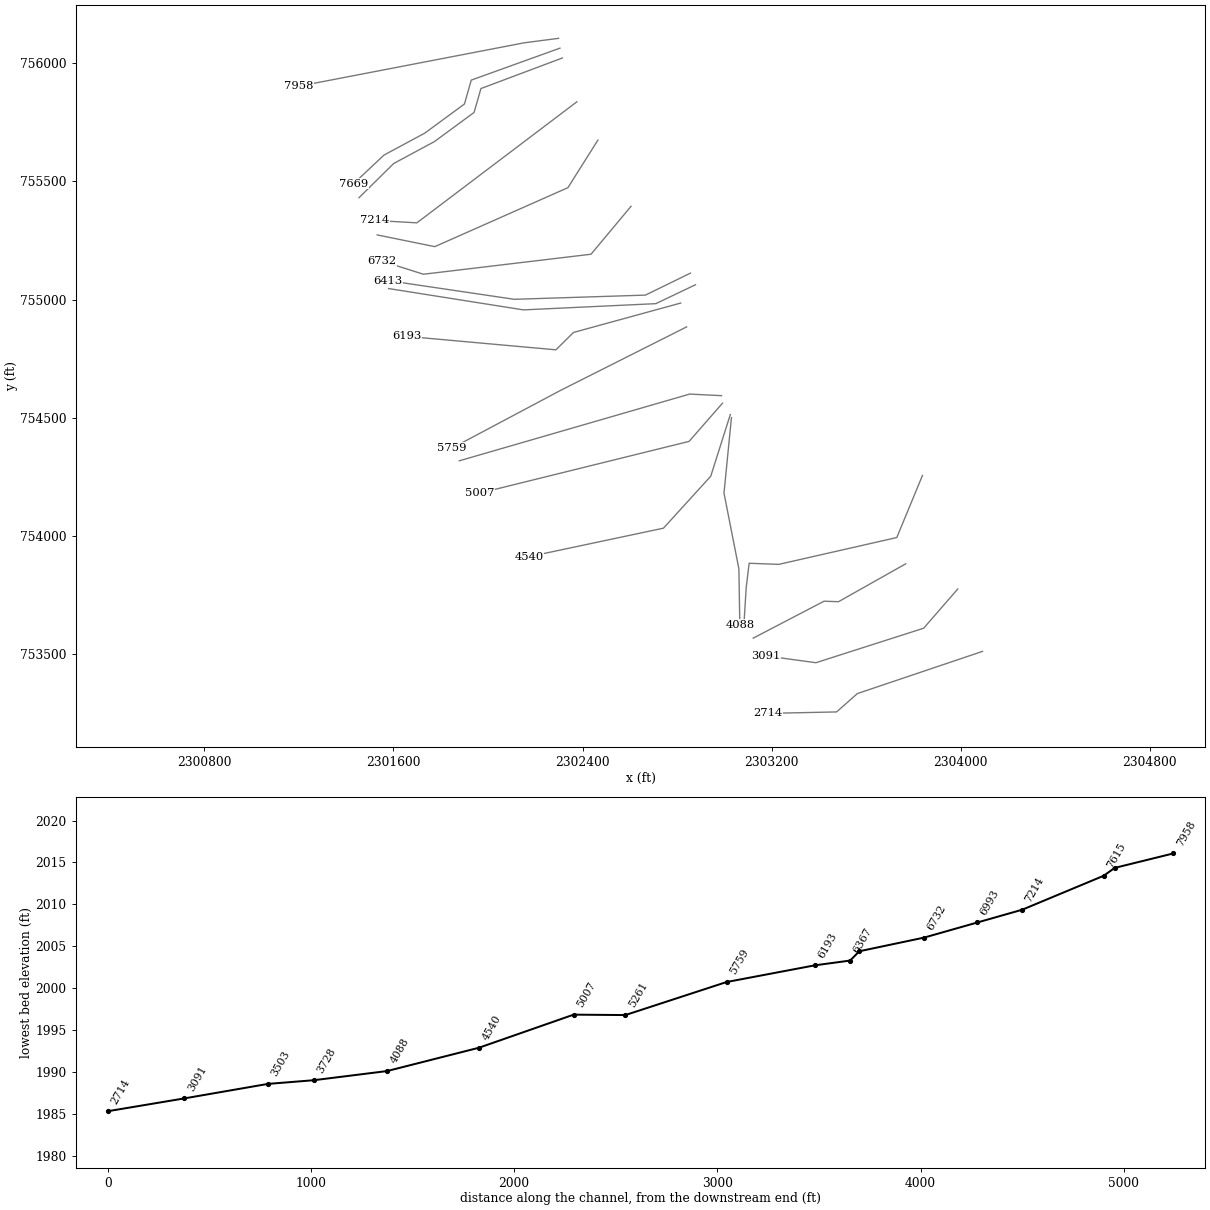
HEC-RAS study SALTLCKRN.prj: SALTLCKRN

--- SALTLCKRN.g01 (geometry) --- (continued)

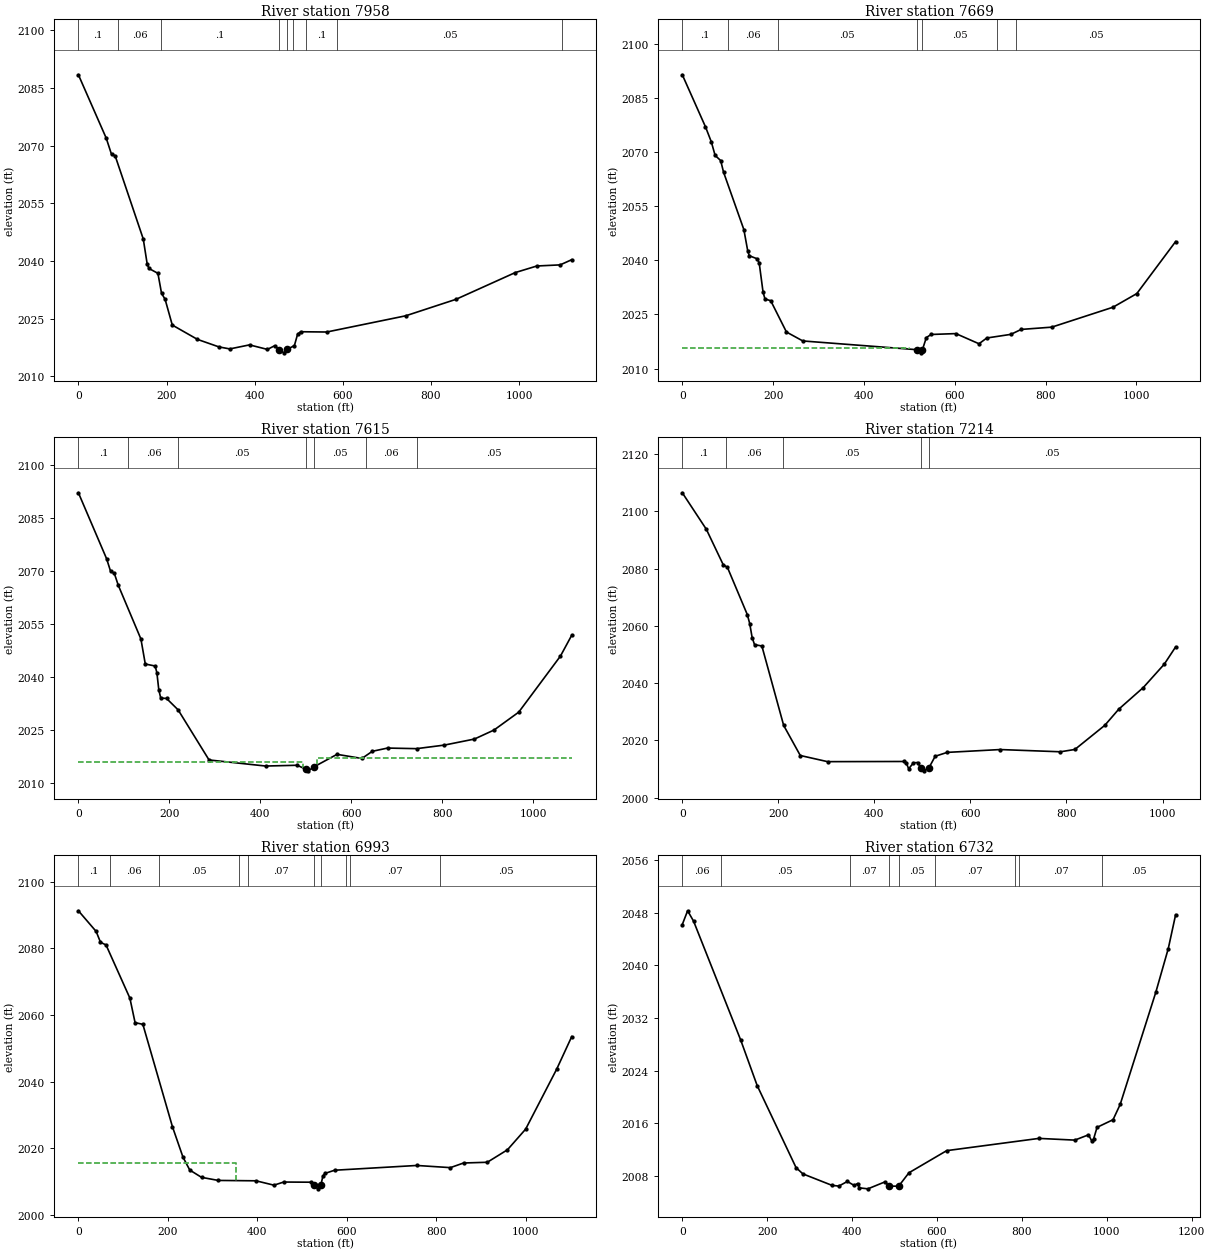
Type RM Length L Ch R = 1 ,7958    ,289.3,289.3,289.3
BEGIN DESCRIPTION:
Structure XS 4
END DESCRIPTION:
XS GIS Cut Line= 3
2302298.78167369756105.4471017082302152.85703088756086.476898142
2301198.50986689755902.611848199
#Sta/Elev= 30
       0 2088.44    63.1 2071.96    75.2 2067.71    83.3 2067.38   147.2 2045.69
     156 2039.23   160.1 2038.03   180.4 2036.77   188.6 2031.57   196.7 2030.01
     213 2023.31   270.1 2019.58   318.9 2017.62   343.5  2017.1   388.2 2018.15
   428.9 2016.97   445.2 2017.93     4552016.938   466.5 2016.08   473.7 2016.97
     490 2017.98   497.2  2020.9   504.1 2021.57   563.4  2021.5   742.6 2025.72
   856.6 2030.01   991.1 2036.97    1040 2038.68  1092.9 2038.97  1119.1 2040.32
#Mann= 9 ,-1,0
       0      .1       0      90     .06       0  187.15      .1       0
     455    .045       0   473.7      .1       0  487.15     .05       0
  517.15      .1       0  587.15     .05       0 1097.15      .1       0
Bank Sta=455,473.7
XS Rating Curve= 0 ,0
Exp/Cntr(USF)=0,0
Exp/Cntr=0.5,0.3

Type RM Length L Ch R = 1 ,7669    ,54.4,54.4,54.4
BEGIN DESCRIPTION:
Structure XS 3 17.4ft
END DESCRIPTION:
XS GIS Cut Line= 6
2302304.56508526756063.9743658672301929.21771903755928.702221982
2301900.32463975755827.5764445132301732.21945123755704.124196695
2301560.12286804755611.5943419642301431.39768098755490.701879603
#Sta/Elev= 30
       0 2091.54    51.1 2077.08    63.8 2072.96    72.3 2069.15    84.5 2067.73
    90.8 2064.53   135.6 2048.56   144.1 2042.67   147.5 2041.31   165.2 2040.44
   169.4 2039.29   177.9 2031.18   182.1 2029.31   194.8 2028.81   229.4 2020.13
   265.4 2017.65   516.1 2015.23   524.7 2014.35     5292015.254   537.5 2018.58
     548 2019.45   602.6 2019.69   653.5 2016.87   670.7 2018.47   723.7 2019.48
   746.4 2020.85   813.7 2021.48   948.6 2027.01  1001.1  2030.8  1086.6 2045.24
#Mann= 7 ,-1,0
       0      .1       0     100     .06       0     210     .05       0
   516.1    .045       0     529     .05       0  692.66     .06       0
  734.58     .05       0
#XS Ineff= 2 , 0
           498.7  2015.8  546.44            2017
Permanent Ineff=
       F       F
Bank Sta=516.1,529
XS Rating Curve= 0 ,0
Exp/Cntr(USF)=0,0
Exp/Cntr=0.5,0.3

Type RM Length L Ch R = 1 ,7615    ,400.9,400.9,400.9
BEGIN DESCRIPTION:
Structure XS 2 23.1ft 7.7
END DESCRIPTION:
XS GIS Cut Line= 6
2302314.69306191756022.3404060472301970.07742545755892.978210196
2301941.18434617755791.8524327272301773.07915765755668.400184909
2301600.98257446755575.8703301782301454.52754329755431.338075681
#Sta/Elev= 30
       0 2092.14    62.1 2073.44    70.6 2069.98    79.1 2069.29    87.6 2065.98
   137.5 2050.73   147.1 2043.65   168.8 2043.09   172.6 2041.18   176.8 2036.35
   181.1 2034.01   193.8 2033.91   219.3 2030.67   287.3 2016.49   411.7 2014.77
   481.4 2014.99   500.62013.819   505.8 2013.41   517.82014.527   568.7 2018.08
   623.4 2016.91   646.3 2018.94   679.8 2019.86   743.7 2019.69   804.8  2020.7
   870.8 2022.41   913.9 2024.96   968.3 2030.03    1060  2045.9  1084.8  2051.8
#Mann= 7 ,-1,0
       0      .1       0     110     .06       0     220     .05       0
   500.6    .045       0   517.8     .05       0  631.69     .06       0
  743.61     .05       0
#XS Ineff= 2 , 0
           492.9  2015.8   525.5            2017
Permanent Ineff=
       F       F
Bank Sta=500.6,517.8
XS Rating Curve= 0 ,0
Exp/Cntr(USF)=0,0
Exp/Cntr=0.5,0.3

Type RM Length L Ch R = 1 ,7214    ,220.7,220.7,220.7
BEGIN DESCRIPTION:
Structure XS 1
END DESCRIPTION:
XS GIS Cut Line= 3
2302376.12173438755836.9457589342301699.03139173755324.750262663
 2301521.0033275 755334.96498766
#Sta/Elev= 30
       0 2106.54    50.1 2093.77    85.2  2081.4      94 2080.46   135.4 2063.95
   140.4 2060.82   145.4 2055.96   150.4 2053.47   165.7 2052.99   211.1 2025.23
   245.7 2014.72   302.5 2012.57   461.4 2012.63   466.4 2012.13   471.4 2010.07
   481.4 2012.17   490.3 2012.27   496.5 2010.41   502.4 2009.36   513.8 2010.49
   526.6 2014.45   551.6 2015.81     662  2016.8   787.4 2016.02   817.5 2016.83
   879.9 2025.28   908.9 2030.91     960 2038.48  1003.7 2046.65  1027.3 2052.67
#Mann= 5 ,-1,0
       0      .1       0      90     .06       0     210     .05       0
   496.5    .045       0   513.8     .05       0
Bank Sta=496.5,513.8
XS Rating Curve= 0 ,0
Exp/Cntr(USF)=0,0
Exp/Cntr=0.3,0.1

Type RM Length L Ch R = 1 ,6993    ,261.5,261.5,261.5
XS GIS Cut Line= 4
2302465.13576649755674.9694054122302338.18132725755473.593398332
2301774.91220599755224.062259123 2301531.2180525755273.676637679
#Sta/Elev= 30
       0 2091.24    39.7 2085.04    49.4 2081.79    61.8 2080.99   115.1 2065.04
   126.7 2057.69   144.1 2057.18   210.2 2026.49   233.8 2017.34     249 2013.47
   275.2 2011.29   312.7 2010.36   397.1 2010.25   437.1 2008.94     459 2009.88
   520.2 2009.83   526.82008.975   535.3 2007.84   542.1 2009.01   546.5 2011.63
   550.9 2012.45   572.7 2013.42   756.5 2014.85   831.6  2014.2     861 2015.59
   914.1 2015.81   959.1 2019.55   999.8 2025.75  1069.2 2043.74  1102.8  2053.5
#Mann= 10 ,-1,0
       0      .1       0      70     .06       0     180     .05       0
  358.05      .1       0  378.05     .07       0   526.8    .045       0
   542.1     .07       0  598.05     .05       0  608.05     .07       0
  808.05     .05       0
#XS Ineff= 2 , 0
           352.5 2015.73
Permanent Ineff=
       F       F
Bank Sta=526.8,542.1
XS Rating Curve= 0 ,0
Exp/Cntr(USF)=0,0
Exp/Cntr=0.3,0.1

Type RM Length L Ch R = 1 ,6732    ,318.9,318.9,318.9
BEGIN DESCRIPTION:
Structure XS 4
END DESCRIPTION:
XS GIS Cut Line= 4
2302605.22342359755394.7940912132302435.95083793755191.958837704
2301726.75707386755107.3225448732301551.64750249755162.773909142
#Sta/Elev= 30
       0 2046.18    12.5 2048.27    26.6 2046.69   137.6 2028.63   176.4 2021.72
     268 2009.26   284.1 2008.31   352.6 2006.57   368.7 2006.46   388.8 2007.16
     405 2006.55     413 2006.85     417 2006.19   437.2 2006.04   477.5  2007.1
   487.32006.443   509.7 2006.45   533.9 2008.48   622.8 2011.84     840  2013.7
   924.6 2013.44   956.8 2014.24   964.9 2013.28   968.9 2013.61     977 2015.38
  1014.7 2016.54  1031.5 2018.86  1115.4 2035.89  1144.8 2042.53  1162.1 2047.67
#Mann= 9 ,-1,0
       0     .06       0      90     .05       0  394.19     .07       0
   487.3    .045       0   509.7     .05       0  594.19     .07       0
  784.19     .05       0  794.19     .07       0  988.41     .05       0
Bank Sta=487.3,509.7
XS Rating Curve= 0 ,0
Exp/Cntr(USF)=0,0
Exp/Cntr=0.5,0.3

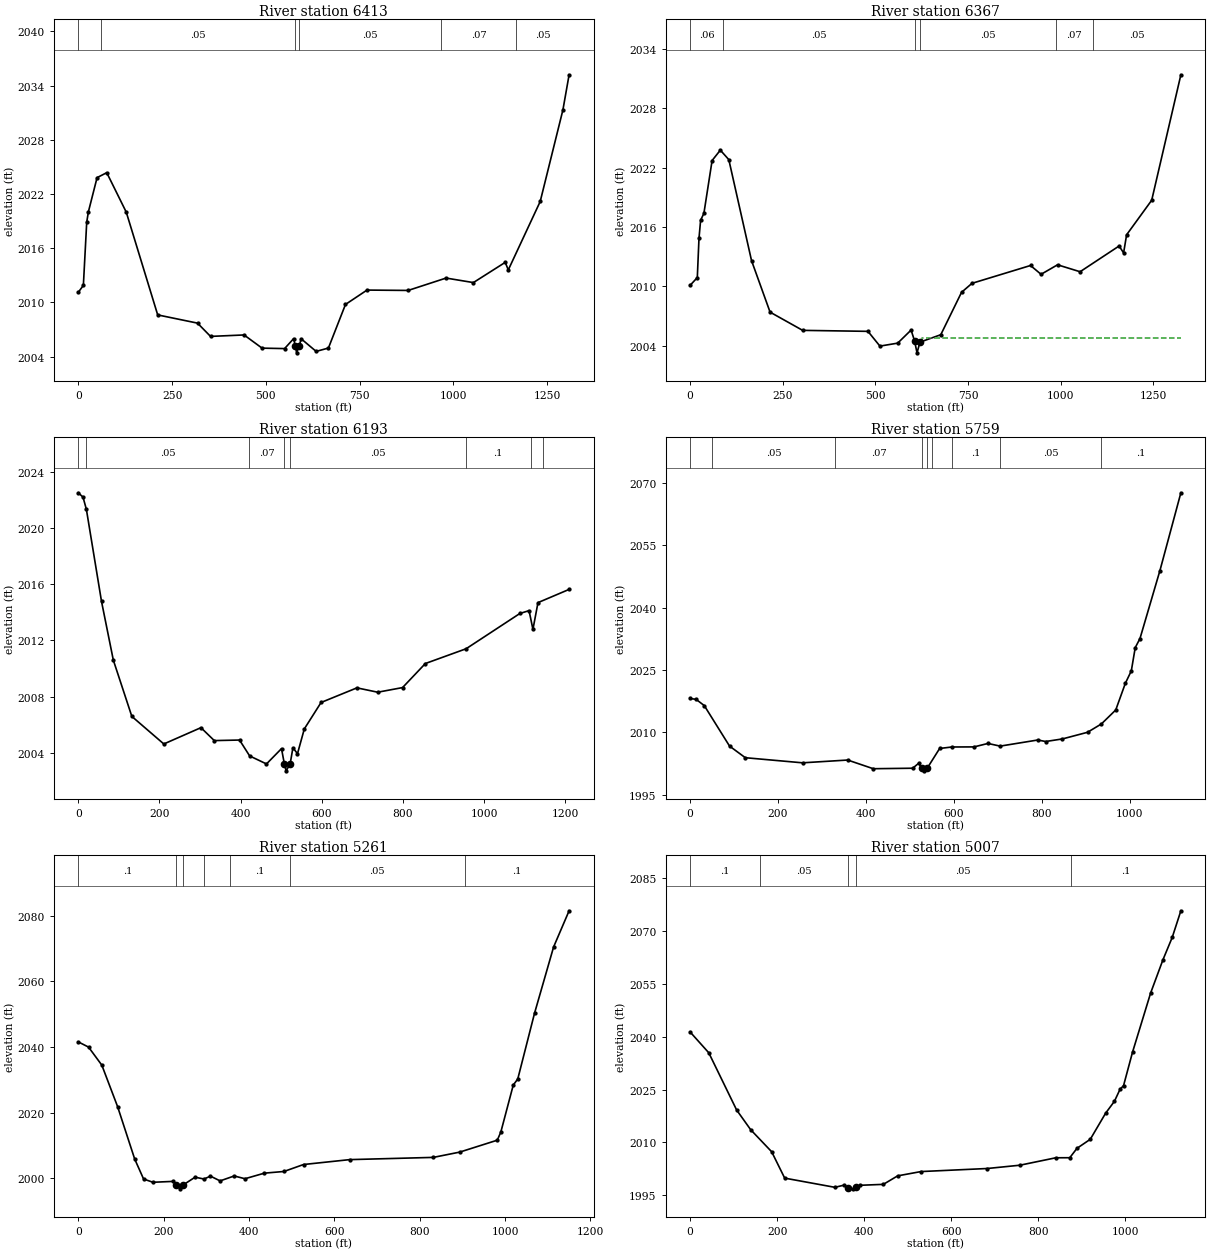
Type RM Length L Ch R = 1 ,6413    ,45.4,45.4,45.4
BEGIN DESCRIPTION:
Structure XS 3 14ft
END DESCRIPTION:
XS GIS Cut Line= 4
2302856.40427504755111.9890140142302666.17376892 755018.98509416
2302111.13481846755001.2423965732301575.79126823755080.463446175
#Sta/Elev= 30
       0 2011.11    13.6 2011.88    22.5 2018.87      27 2020.03    50.1 2023.81
    75.9 2024.36   127.9 2019.99   211.7 2008.61   317.8  2007.7   352.5 2006.23
   441.9 2006.39   489.9 2004.93   549.9 2004.88   573.9 2005.98   578.82005.123
   581.9 2004.41   589.22005.198   593.9 2005.97     634 2004.57   666.7 2004.94
   712.2 2009.77   769.6 2011.36   879.2 2011.32   980.3 2012.69  1053.1 2012.19
    1138 2014.43  1146.1 2013.59  1231.2 2021.17  1291.7 2031.31  1308.2  2035.2
#Mann= 6 ,-1,0
       0     .06       0      60     .05       0   578.8    .045       0
   589.2     .05       0  967.07     .07       0 1167.07     .05       0
#XS Ineff= 2 , 0
          564.79 2004.79  603.17         2004.79
Permanent Ineff=
       F       F
Bank Sta=578.8,589.2
XS Rating Curve= 0 ,0
Exp/Cntr(USF)=0,0
Exp/Cntr=0.5,0.3

Type RM Length L Ch R = 1 ,6367    ,174,174,174
BEGIN DESCRIPTION:
Structure XS 2 12.6ft 4.2
END DESCRIPTION:
XS GIS Cut Line= 4
2302877.89557973755062.8450680522302710.12287613754982.843033872
2302149.91390313754956.4836320522301579.55272881755046.685365101
#Sta/Elev= 30
       0 2010.11    19.6  2010.9    24.1 2014.85    28.5 2016.69    37.4 2017.39
    59.5 2022.72    81.7 2023.77   104.6 2022.81   165.9 2012.61   215.9 2007.41
   303.8 2005.57     480 2005.47   512.2 2003.98   560.2 2004.28   596.3  2005.6
   605.6 2004.52   612.3  2003.3   620.3 2004.38   676.4 2005.13   732.4 2009.41
   760.6 2010.32   918.5 2012.12   946.9 2011.23   991.4 2012.19  1052.2 2011.49
  1157.5 2014.09  1169.6 2013.39  1177.7 2015.22  1245.4 2018.71  1324.1 2031.38
#Mann= 6 ,-1,0
       0     .06       0      90     .05       0   605.6    .045       0
   620.3     .05       0   986.7     .07       0  1086.7     .05       0
#XS Ineff= 2 , 0
          601.38 2004.79   624.5         2004.79
Permanent Ineff=
       F       F
Bank Sta=605.6,620.3
XS Rating Curve= 0 ,0
Exp/Cntr(USF)=0,0
Exp/Cntr=0.5,0.3

Type RM Length L Ch R = 1 ,6193    ,433.9,433.9,433.9
BEGIN DESCRIPTION:
Structure XS 1
END DESCRIPTION:
XS GIS Cut Line= 4
  2302815.453669754985.4194456242302361.80894098754860.982131727
2302287.40673572754787.498472213 2301655.4472639754844.448308336
#Sta/Elev= 30
       0  2022.5    11.7 2022.19      20 2021.32    57.3 2014.77    86.4  2010.6
     132  2006.6   210.8 2004.64   302.3  2005.8   335.2 2004.88   397.4 2004.92
   422.3 2003.79   463.8 2003.22   500.8 2004.31   507.8 2003.23   512.1 2002.73
     5222003.206   528.9 2004.37   540.2 2003.95     557 2005.71   598.3 2007.59
   686.7 2008.63   737.9 2008.32   799.1 2008.65   855.3 2010.36   955.7 2011.41
  1088.3 2013.92  1110.8 2014.12  1120.4 2012.79  1132.8 2014.69  1209.5 2015.63
#Mann= 8 ,-1,0
       0     .06       0      20     .05       0     420     .07       0
   507.8    .045       0     522     .05       0  954.98      .1       0
 1114.98     .07       0 1144.98     .05       0
Bank Sta=507.8,522
XS Rating Curve= 0 ,0
Exp/Cntr(USF)=0,0
Exp/Cntr=0.3,0.1

Type RM Length L Ch R = 1 ,5759    ,498.1,498.1,498.1
XS GIS Cut Line= 3
  2302840.401825754884.4928145022302308.53328783754616.648963843
2301848.74093933754372.226781502
#Sta/Elev= 30
       0 2018.15    13.7 2017.95    32.4 2016.44    89.8  2006.7   125.7  2003.9
   255.8 2002.67   358.5 2003.34   416.7 2001.25   506.3 2001.37   519.8 2002.55
   526.9 2001.36   532.1 2000.74     5392001.313   567.6 2006.12   595.5 2006.48
   645.7  2006.5   677.5 2007.33   705.2 2006.69   790.7 2008.16   808.8  2007.8
   846.8 2008.42     904 2010.02   935.5 2012.03   968.1 2015.39     990 2021.83
  1003.5  2024.8  1012.4 2030.39  1023.2 2032.58  1068.6 2048.95  1116.2 2067.66
#Mann= 9 ,-1,0
       0     .06       0      50     .05       0     330     .07       0
   526.9    .045       0     539     .07       0     550     .05       0
   595.5      .1       0   705.5     .05       0   935.5      .1       0
Bank Sta=526.9,539
XS Rating Curve= 0 ,0
Exp/Cntr(USF)=0,0
Exp/Cntr=0.3,0.1

Type RM Length L Ch R = 1 ,5261    ,254.4,254.4,254.4
XS GIS Cut Line= 3
2302988.25461773754593.5047246092302853.27381653754600.251821034
2301878.51870239 754317.87022726
#Sta/Elev= 30
       0 2041.57    24.1 2039.98    55.2 2034.48    92.2 2021.82   132.2 2005.88
     153  1999.8   174.9  1998.8   222.5 1999.07   229.91997.897   238.6  1996.8
   245.1 1997.93   273.7 2000.35   294.5 1999.79   309.7 2000.67   332.3 1999.22
   365.3 2000.72   390.6 1999.88   436.1 2001.58   481.9 2002.09   527.8 2004.21
   635.8  2005.7   831.8 2006.38   893.7 2007.99   981.7 2011.62     990 2014.08
  1019.2 2028.43  1029.7 2030.26  1069.1 2050.34  1113.7 2070.49    1150 2081.51
#Mann= 7 ,-1,0
       0      .1       0   229.9    .045       0   245.1      .1       0
  295.15     .07       0  355.15      .1       0  495.15     .05       0
  905.15      .1       0
Bank Sta=229.9,245.1
XS Rating Curve= 0 ,0
Exp/Cntr(USF)=0,0
Exp/Cntr=0.3,0.1

Type RM Length L Ch R = 1 ,5007    ,466.5,466.5,466.5
BEGIN DESCRIPTION:
Structure
END DESCRIPTION:
XS GIS Cut Line= 3
2302992.28796037754561.7399506842302850.80256989 754400.08084324
2301964.32275439754180.937648025
#Sta/Elev= 30
       0 2041.38      43 2035.46   107.1 2019.21   139.4 2013.62   187.6 2007.37
   217.5 1999.89   332.9 1997.28   353.5 1997.89   362.81997.217   374.1 1996.85
   380.51997.239   391.2 1997.86   444.2 1998.12   477.1 2000.53   530.7 2001.75
   683.1 2002.62   757.9 2003.55   840.5 2005.66   872.7 2005.68   889.2 2008.34
   919.8 2010.91   955.1 2018.32   975.3 2021.69   988.1 2025.07   996.3 2026.15
  1016.9 2035.63  1058.5 2052.41  1086.9 2061.87  1108.1 2068.18    1128 2075.74
#Mann= 5 ,-1,0
       0      .1       0     160     .05       0   362.8    .045       0
   380.5     .05       0  874.83      .1       0
Bank Sta=362.8,380.5
XS Rating Curve= 0 ,0
Exp/Cntr(USF)=0,0
Exp/Cntr=0.3,0.1

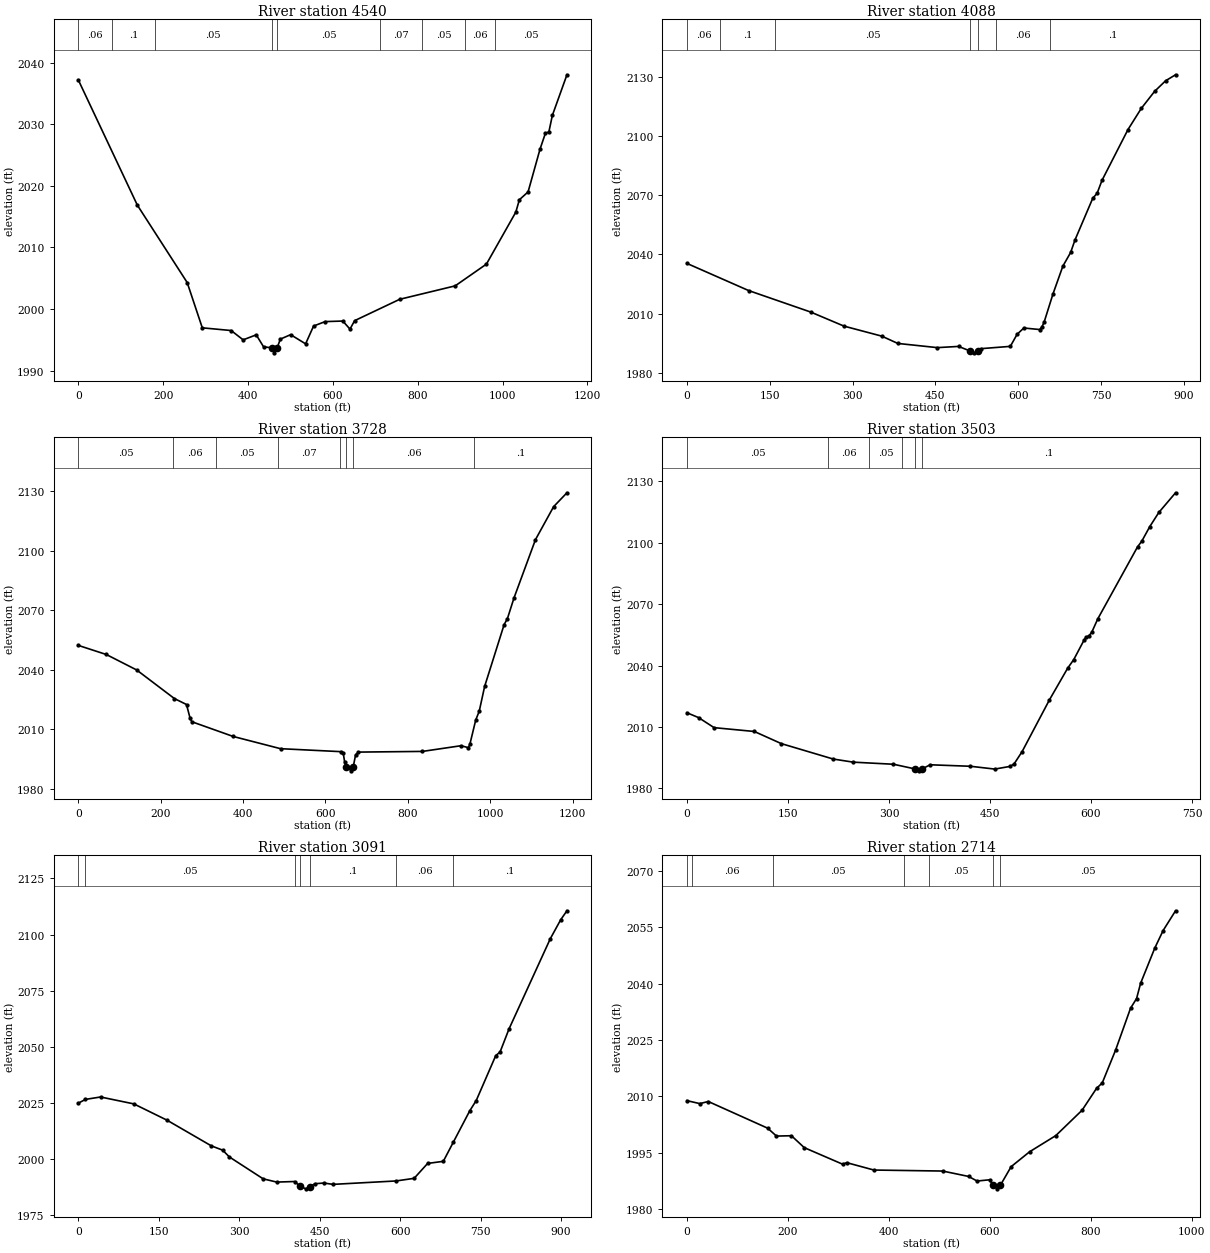
Type RM Length L Ch R = 1 ,4540    ,452,452,452
XS GIS Cut Line= 4
 2303025.3714325754513.8941072192302942.50064769754252.670981198
2302742.43030457754032.8681989762302174.56606934753912.464569471
#Sta/Elev= 30
       0  2037.2   139.2 2016.87   256.7 2004.31   292.3 1996.96   360.3 1996.52
   388.6 1995.01   419.4 1995.82   436.7 1993.88   456.8 1993.71   462.2  1992.9
   468.71993.734   476.4 1995.13   500.5 1995.85   535.8 1994.36   554.6 1997.25
   581.8 1997.97   623.5 1998.06   640.4 1996.75   651.3 1998.12   757.6 2001.59
   888.4 2003.77     962  2007.3  1031.3 2015.74  1039.7 2017.75  1060.2 2019.02
  1088.3 2025.95  1101.1 2028.55  1109.2 2028.75  1117.4 2031.43  1151.8 2038.03
#Mann= 9 ,-1,0
       0     .06       0      80      .1       0     180     .05       0
   456.8    .045       0   468.7     .05       0  711.28     .07       0
  811.28     .05       0  911.28     .06       0  981.28     .05       0
Bank Sta=456.8,468.7
XS Rating Curve= 0 ,0
Exp/Cntr(USF)=0,0
Exp/Cntr=0.3,0.1

Type RM Length L Ch R = 1 ,4088    ,360.3,360.3,360.3
XS GIS Cut Line= 4
2303030.05902955754500.446023788 2302998.5393067754181.308829948
 2303061.5787524753860.8583143232303065.51871776753623.147071174
#Sta/Elev= 30
       0  2035.4   111.8 2021.65   224.4 2010.75   284.6 2003.64   352.9 1998.58
     382 1994.88   453.5 1992.76     492 1993.37   512.4 1991.11   520.6 1990.12
   526.9 1990.88   532.8 1992.24   585.8  1993.4   598.1 1999.54   610.3 2002.69
   638.8 2001.92   642.9 2003.16     647 2005.68     663 2019.91   680.9 2033.99
     695 2040.93     703 2047.34     735 2068.33     743 2070.91   751.8 2077.43
   798.9 2103.17     823 2113.88     847 2122.46     867 2127.85     885 2130.88
#Mann= 7 ,-1,0
       0     .06       0      60      .1       0     160     .05       0
   512.4    .045       0   526.9     .05       0  560.69     .06       0
  657.28      .1       0
Bank Sta=512.4,526.9
XS Rating Curve= 0 ,0
Exp/Cntr(USF)=0,0
Exp/Cntr=0.3,0.1

Type RM Length L Ch R = 1 ,3728    ,225.4,225.4,225.4
BEGIN DESCRIPTION:
Structure
END DESCRIPTION:
XS GIS Cut Line= 6
  2303838.318506 754255.901184962303729.68571635753993.236827898
2303230.58162444753879.7576764652303104.97322382753884.311677415
2303092.52201073753781.8725781582303082.59450885753620.964870762
#Sta/Elev= 30
       0 2052.27      68 2047.68   141.7 2039.88   233.4 2025.45   262.7 2022.47
   271.3 2015.63   275.6 2013.78     376 2006.36   490.9  2000.2   638.6 1998.69
   643.2  1997.9   646.5 1993.59   649.9 1991.03   663.1 1989.03   667.3 1990.91
   673.2  1997.1   679.9 1998.48   835.3 1998.82   928.9 2001.69   946.9 2000.72
   950.5 2002.36   964.8 2014.67   973.3 2019.09   986.4 2031.59  1033.7 2062.74
  1041.7 2065.76  1057.7  2076.2  1109.8 2105.57  1153.9 2122.21  1186.2  2129.2
#Mann= 8 ,-1,0
       0     .05       0     230     .06       0  334.24     .05       0
  484.24     .07       0  634.24     .06       0   649.9    .045       0
   667.3     .06       0  961.78      .1       0
Bank Sta=649.9,667.3
XS Rating Curve= 0 ,0
Exp/Cntr(USF)=0,0
Exp/Cntr=0.3,0.1

Type RM Length L Ch R = 1 ,3503    ,411.8,411.8,411.8
XS GIS Cut Line= 4
2303767.34183978753881.9934956032303483.08435609  753721.7873737
2303421.84797316753723.8285864642303122.16107808753567.584819379
#Sta/Elev= 30
       0 2016.98    17.4 2014.59    40.4 2009.69   100.1 2007.82   140.2 2001.89
   217.3 1994.35     247 1992.83   306.7 1991.81   338.2 1989.56   345.2 1988.59
   349.41989.559   361.2 1991.55     421 1990.82   457.1 1989.45   479.7 1990.75
   485.7 1991.92   497.7 1997.99   538.3 2023.28   565.4 2038.78   574.4 2042.95
   589.4  2052.3   592.4 2053.85     597  2054.6     601 2056.23   610.2 2062.94
   669.1 2098.03   675.4  2100.8   687.3 2107.94   700.7 2114.83   725.5 2124.44
#Mann= 6 ,-1,0
       0     .05       0     210     .06       0     270     .05       0
     320      .1       0   338.2    .045       0   349.4      .1       0
Bank Sta=338.2,349.4
XS Rating Curve= 0 ,0
Exp/Cntr(USF)=0,0
Exp/Cntr=0.3,0.1

Type RM Length L Ch R = 1 ,3091    ,377.2,377.2,377.2
XS GIS Cut Line= 4
2303987.39315178753775.2631991582303843.27004777753609.521629545
2303387.48073133753463.5969867332303176.70069171753492.421607535
#Sta/Elev= 30
       0 2024.98    13.4 2026.67    41.5 2027.74   103.5 2024.67   165.4 2017.42
   248.1 2005.98   269.1 2004.08   281.7 2001.05   344.7 1991.31   369.9 1989.87
   403.5 1990.12   413.91987.914   424.5 1986.86   432.3  1987.9   441.3 1989.15
   458.1 1989.44   474.9 1988.85   592.5 1990.37   626.1 1991.53   651.3 1998.17
   680.5  1999.1     699 2007.54   729.8 2021.58   741.9 2026.17   778.3 2046.17
   786.3 2047.74   803.1 2058.08   880.1 2098.24   899.4 2106.64     911 2110.62
#Mann= 7 ,-1,0
       0     .06       0    13.4     .05       0   403.5      .1       0
   413.9    .045       0   432.3      .1       0   592.5     .06       0
     699      .1       0
Bank Sta=413.9,432.3
XS Rating Curve= 0 ,0
Exp/Cntr(USF)=0,0
Exp/Cntr=0.3,0.1

Type RM Length L Ch R = 1 ,2714    ,354,354,354
XS GIS Cut Line= 4
2304092.38636623753511.542458979 2303562.6916539753332.936342105
2303474.91950503753255.3702570622303183.02607974753249.246618769
#Sta/Elev= 30
       0 2008.83    25.6 2008.04    42.4  2008.6   159.9  2001.5   177.5 1999.39
   207.1 1999.48   232.5 1996.31   308.4  1991.9   316.8  1992.3   370.5 1990.34
   506.8 1990.07   558.2 1988.63   574.8 1987.41   599.7 1987.74   605.9 1986.46
   614.4 1985.33   621.1 1986.29   642.4 1991.24   678.9  1995.2   730.9 1999.52
   782.9 2006.27   811.6 2012.11   822.9 2013.55   849.5 2022.36   878.9 2033.44
   890.9 2036.04   898.9 2040.11   926.9 2049.46   943.5 2054.16   968.1 2059.42
#Mann= 7 ,-1,0
       0     .05       0      10     .06       0     170     .05       0
     430      .1       0     480     .05       0   605.9    .045       0
   621.1     .05       0
Bank Sta=605.9,621.1
XS Rating Curve= 0 ,0
Exp/Cntr(USF)=0,0
Exp/Cntr=0.3,0.1