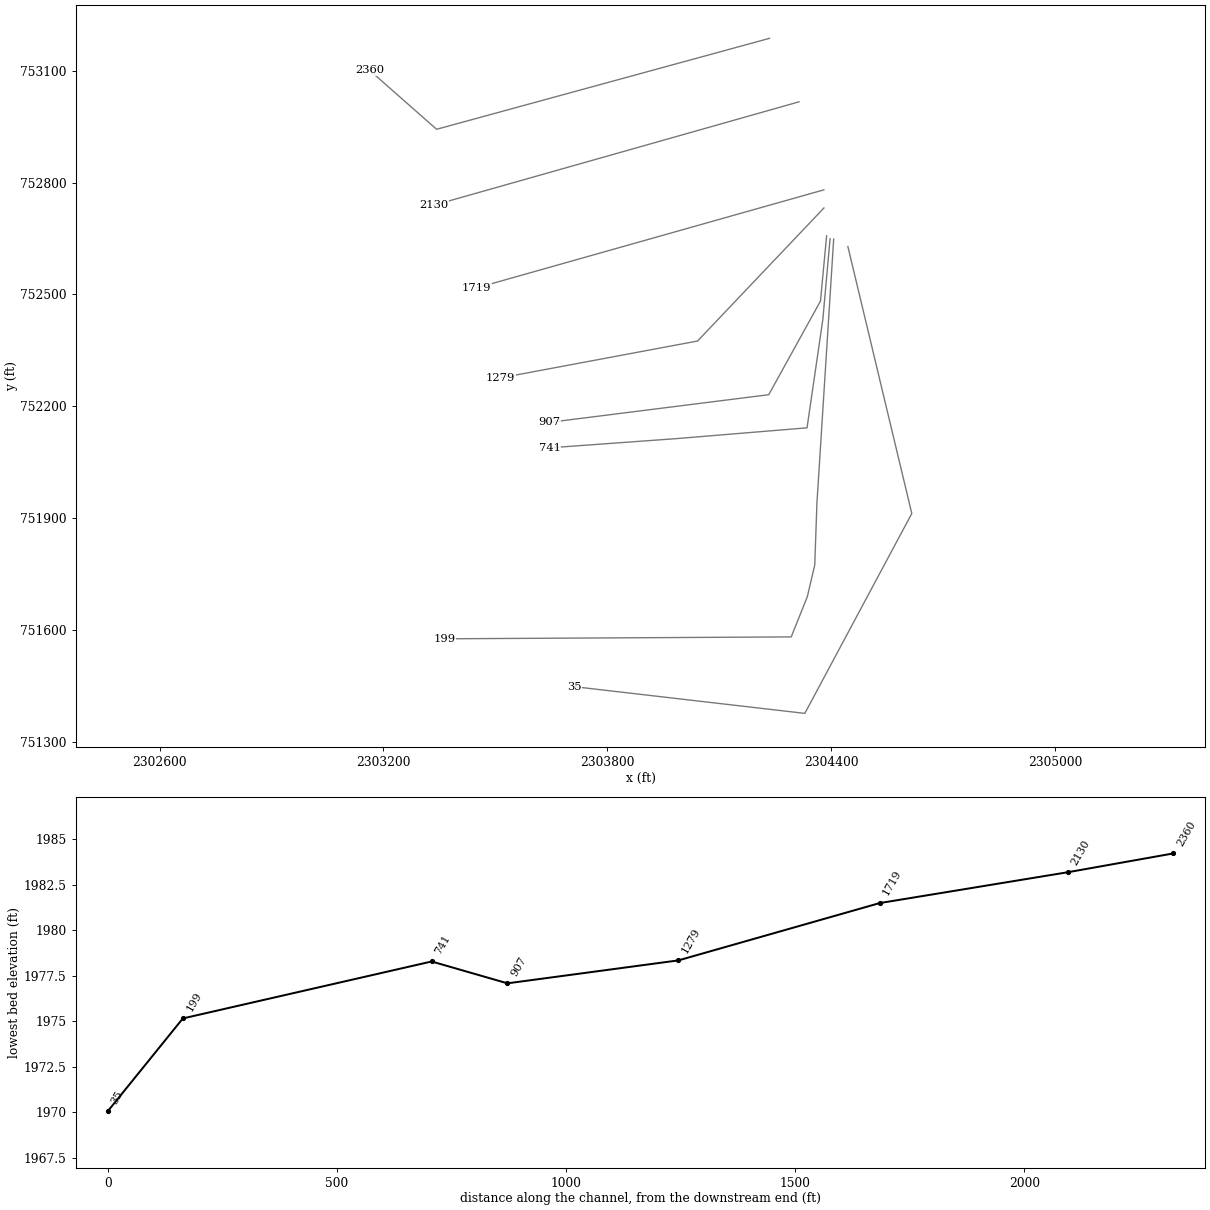
HEC-RAS study SALTLCKRN.prj: SALTLCKRN

--- SALTLCKRN.g01 (geometry) --- (continued)

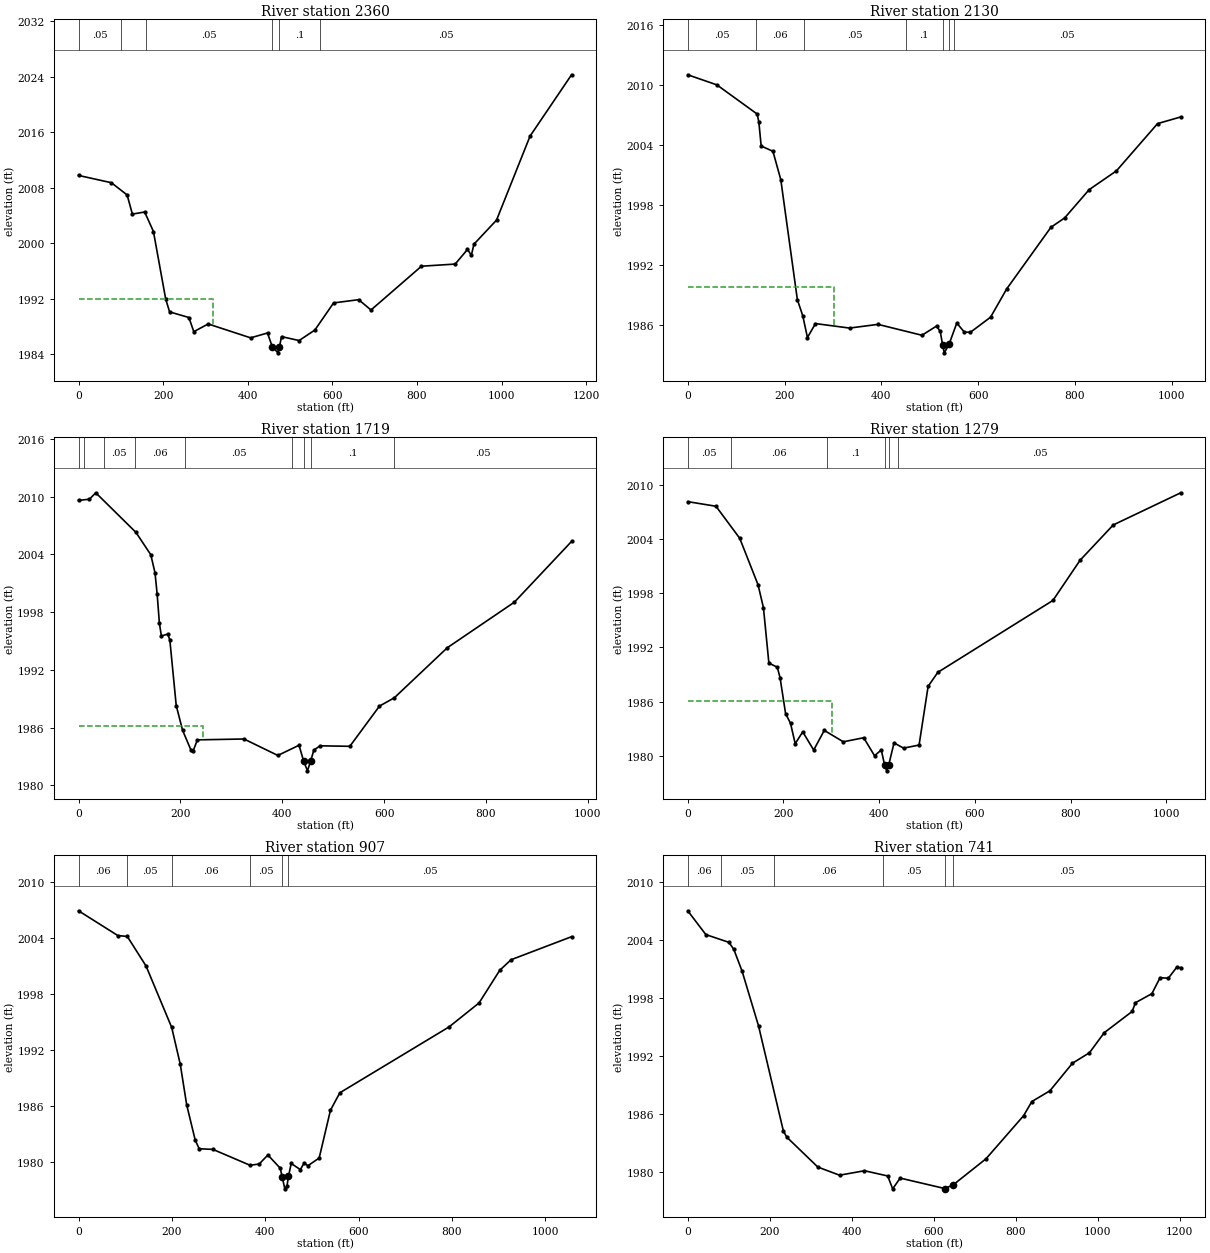
Type RM Length L Ch R = 1 ,2360    ,229.4,229.4,229.4
XS GIS Cut Line= 3
2304235.00591659753186.8021081112303342.44226132 752942.95227349
2303162.28838131753101.487687903
#Sta/Elev= 30
       0 2009.79    77.6 2008.74   114.9 2006.98   127.3 2004.22   156.4 2004.52
   177.1 2001.71   206.1 1991.97   215.3 1990.13   260.9 1989.32   272.5 1987.28
   306.5 1988.39   406.8 1986.39   446.7 1987.09   458.1 1985.08   471.5 1984.23
   474.8 1985.03   479.8 1986.57   521.3    1986   558.6 1987.51   602.9 1991.42
   662.2 1991.89   691.3  1990.4   810.6 1996.71   890.3 1997.02   919.3 1999.12
   928.5  1998.3   934.7 1999.89     988 2003.35  1067.3 2015.46  1165.3 2024.29
#Mann= 6 ,-1,0
       0     .05       0     100     .06       0     160     .05       0
   458.1    .045       0   474.8      .1       0     570     .05       0
#XS Ineff= 2 , 0
          319.03 1991.97
Permanent Ineff=
       F       F
Bank Sta=458.1,474.8
XS Rating Curve= 0 ,0
Exp/Cntr(USF)=0,0
Exp/Cntr=0.3,0.1

Type RM Length L Ch R = 1 ,2130    ,411.5,411.5,411.5
XS GIS Cut Line= 2
 2304314.1089766753016.5709628132303334.07186932 752739.13398759
#Sta/Elev= 30
       0 2011.04    60.2 2010.03   143.4 2007.11   146.9 2006.32   151.7 2003.91
     176 2003.38   192.2 2000.55   226.5 1988.52   237.6 1986.92   247.3 1984.73
   263.9 1986.13   334.2 1985.68   393.1 1986.05   483.8 1984.96     514 1985.88
   521.7 1985.34   526.4 1984.02     530  1983.2   539.7 1984.04   555.8 1986.18
   571.5 1985.27     584 1985.26   625.6 1986.77   658.9  1989.6   750.3 1995.77
   778.7 1996.71   829.3 1999.54   885.6 2001.42   970.6 2006.15  1018.5 2006.82
#Mann= 7 ,-1,0
       0     .05       0     140     .06       0     240     .05       0
     450      .1       0   526.4    .045       0   539.7      .1       0
     550     .05       0
#XS Ineff= 2 , 0
          301.13 1989.75
Permanent Ineff=
       F       F
Bank Sta=526.4,539.7
XS Rating Curve= 0 ,0
Exp/Cntr(USF)=0,0
Exp/Cntr=0.3,0.1

Type RM Length L Ch R = 1 ,1719    ,439.3,439.3,439.3
XS GIS Cut Line= 2
2304380.76591221752780.5693799932303449.37035253752517.544715172
#Sta/Elev= 30
       0 2009.61    21.4 2009.73    33.9  2010.4   112.8 2006.28   141.9 2003.96
   150.2 2002.07   154.4 1999.86   158.8 1996.82   162.7 1995.52   175.2 1995.71
   179.3 1995.09   191.8 1988.29   204.3 1985.71   220.9 1983.64   225.1 1983.57
   233.3 1984.72   324.8 1984.81   391.3  1983.1   432.9 1984.16   441.9 1982.51
   449.5  1981.5   455.71982.524     462 1983.66   474.4  1984.1   532.6 1984.05
   590.8 1988.23   619.9 1989.09   723.8 1994.29   855.6 1999.03   967.8 2005.34
#Mann= 9 ,-1,0
       0     .05       0      10     .06       0      50     .05       0
     110     .06       0     210     .05       0     420      .1       0
   441.9    .045       0   455.7      .1       0     620     .05       0
#XS Ineff= 2 , 0
          244.19 1986.18
Permanent Ineff=
       F       F
Bank Sta=441.9,455.7
XS Rating Curve= 0 ,0
Exp/Cntr(USF)=0,0
Exp/Cntr=0.3,0.1

Type RM Length L Ch R = 1 ,1279    ,372.8,372.8,372.8
XS GIS Cut Line= 3
2304380.94606609752731.9278323892304042.07661778 752375.22314996
2303513.50513381752276.318669832
#Sta/Elev= 30
       0 2008.11      59  2007.6   108.6 2004.06   146.8 1998.93   158.1  1996.4
   169.5 1990.26     187 1989.81   192.8 1988.66   204.4 1984.68   214.7  1983.6
   224.5 1981.35   240.2 1982.66   263.1 1980.65   285.2 1982.82     325 1981.56
   367.5 1982.01   390.2 1980.02   404.3 1980.66   411.11979.015   415.6 1978.35
   419.91979.019   430.9 1981.44   450.7 1980.86   483.2  1981.2   502.1 1987.69
   522.4 1989.24   762.8 1997.19   819.5 2001.63   888.7 2005.53  1029.8 2009.09
#Mann= 6 ,-1,0
       0     .05       0      90     .06       0     290      .1       0
   411.1    .045       0   419.9      .1       0     440     .05       0
#XS Ineff= 2 , 0
          301.65 1986.05
Permanent Ineff=
       F       F
Bank Sta=411.1,419.9
XS Rating Curve= 0 ,0
Exp/Cntr(USF)=0,0
Exp/Cntr=0.3,0.1

Type RM Length L Ch R = 1 ,907     ,165.4,165.4,165.4
XS GIS Cut Line= 4
2304388.14834223752657.2522215262304371.63876874752482.250742469
2304232.95835137752231.3052253312303643.56657756752157.012144599
#Sta/Elev= 30
       0 2006.91    84.4 2004.25   104.5 2004.16   144.7 2000.99   199.7  1994.4
   218.1 1990.44   231.8  1986.1   250.1 1982.31   258.6 1981.39     288 1981.32
   367.5 1979.62   387.2 1979.75   405.8 1980.72   432.3  1979.3  436.29  1978.4
   442.1 1977.09   446.6 1977.36   449.9 1978.42   455.8 1979.81   475.4 1979.15
   483.4 1979.86   491.5 1979.57   515.7 1980.39   539.9 1985.52     560 1987.39
   793.9 1994.45   858.4 1997.03   902.7 2000.53   926.9 2001.66  1056.5 2004.13
#Mann= 6 ,-1,0
       0     .06       0   104.5     .05       0   199.7     .06       0
   367.5     .05       0  436.29    .045       0   449.9     .05       0
Bank Sta=436.29,449.9
XS Rating Curve= 0 ,0
Exp/Cntr(USF)=0,0
Exp/Cntr=0.3,0.1

Type RM Length L Ch R = 1 ,741     ,542.8,542.8,542.8
XS GIS Cut Line= 5
2304397.38994113752649.1727679882304378.04536776 752433.40637274
2304335.63611076752142.4937501812303984.45770194 752113.47689013
2303645.92766802752088.924162395
#Sta/Elev= 30
       0 2007.02    44.2 2004.56   100.4 2003.76   112.4 2003.03   132.5 2000.79
   172.7 1995.12     233 1984.31   241.1 1983.65   317.3 1980.54   370.2  1979.7
   431.1 1980.16   487.7 1979.62   499.8 1978.29   518.1  1979.4   626.61978.324
   646.61978.675   727.3 1981.39   819.2 1985.85   839.2 1987.31   883.3 1988.42
   938.3 1991.27   979.7 1992.35  1015.7 1994.42  1083.9 1996.62  1091.9 1997.52
    1132 1998.46    1152 2000.11  1172.1 2000.05  1192.1 2001.16  1202.4 2001.15
#Mann= 6 ,-1,0
       0     .06       0      80     .05       0     210     .06       0
  476.63     .05       0   626.6    .045       0   646.6     .05       0
Bank Sta=626.6,646.6
XS Rating Curve= 0 ,0
Exp/Cntr(USF)=0,0
Exp/Cntr=0.3,0.1

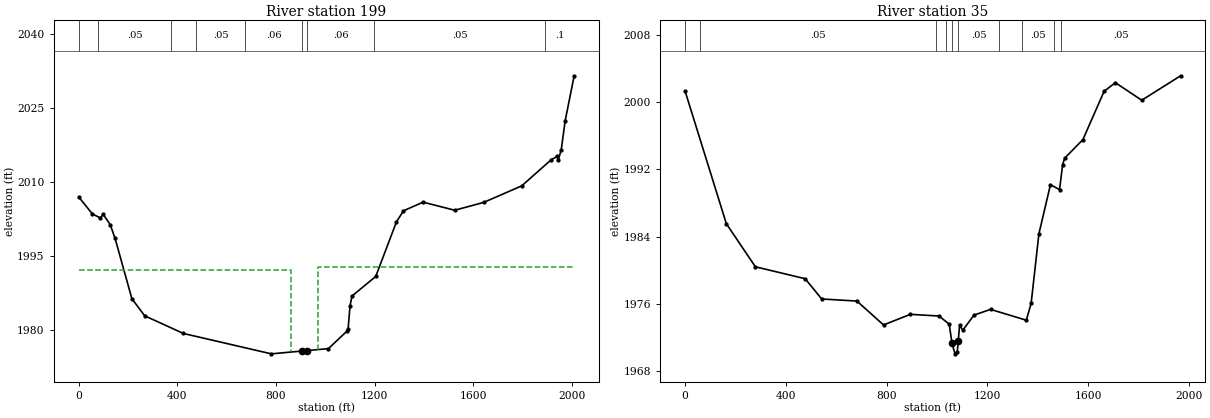
Type RM Length L Ch R = 1 ,199     ,163.8,163.8,163.8
BEGIN DESCRIPTION:
Structure
END DESCRIPTION:
XS GIS Cut Line= 6
2304407.10770653752648.7000569972304362.16543191751940.689869932
2304356.30907116751774.6634532372304336.49214436 751689.99112963
2304293.25521316751581.8988016212303363.81532071 751576.82117021
#Sta/Elev= 30
       0 2006.99    55.6 2003.53    87.7 2002.71    99.7 2003.43   127.8 2001.38
   147.8 1998.56   215.9 1986.33     268 1982.86   424.7 1979.29     781 1975.16
   905.91975.731   926.5 1975.82  1012.5 1976.22  1088.2 1979.79  1092.2 1980.19
  1100.2 1984.95  1108.2 1986.89  1204.2 1990.84  1288.2 2001.91  1316.8 2004.16
  1396.2 2005.91  1524.2 2004.27  1641.9 2005.86  1796.2 2009.22  1916.2 2014.54
  1940.3 2015.19  1944.2 2014.44  1956.2 2016.53  1972.2 2022.44  2008.6 2031.53
#Mann= 9 ,-1,0
       0     .06       0      80     .05       0  375.78     .06       0
  475.78     .05       0  675.78     .06       0   905.9    .045       0
   926.5     .06       0 1199.14     .05       0 1889.14      .1       0
#XS Ineff= 2 , 0
          859.96  1992.2  970.42         1992.86
Permanent Ineff=
       F       F
Bank Sta=905.9,926.5
XS Rating Curve= 0 ,0
Exp/Cntr(USF)=0,0
Exp/Cntr=0.3,0.1

Type RM Length L Ch R = 1 ,35      ,,,
XS GIS Cut Line= 4
2304445.17534023752628.4738663282304616.51281714751912.739335047
2304329.70921744751376.8650129832303710.79014348 751448.52011732
#Sta/Elev= 30
       0 2001.32   163.8 1985.54     279 1980.42   476.5    1979   542.2 1976.59
     682 1976.34   787.5  1973.5   894.2 1974.76  1007.7 1974.56  1048.5 1973.59
1059.1711971.313  1071.2 1970.06  1080.3 1970.32  1084.2 1971.59  1089.3 1973.45
  1102.3 1972.88  1146.7 1974.67  1212.4 1975.35  1354.3 1974.06  1373.5 1976.08
  1404.3 1984.35  1450.1 1990.19  1486.2  1989.6  1498.3 1992.54  1506.4 1993.34
  1578.8 1995.55    1663  2001.3  1707.7 2002.33  1812.4 2000.24  1966.8 2003.15
#Mann= 10 ,-1,0
       0     .06       0      60     .05       0  995.96      .1       0
 1035.96     .05       01059.171    .045       0  1084.2     .05       0
 1245.96     .06       0 1335.96     .05       0 1463.75     .06       0
 1493.75     .05       0
Bank Sta=1059.171,1084.2
XS Rating Curve= 0 ,0
Exp/Cntr(USF)=0,0
Exp/Cntr=0.3,0.1
LCMann Table=0

Chan Stop Cuts=-1
Use User Specified Reach Order=0
Composite Channel Slope=5